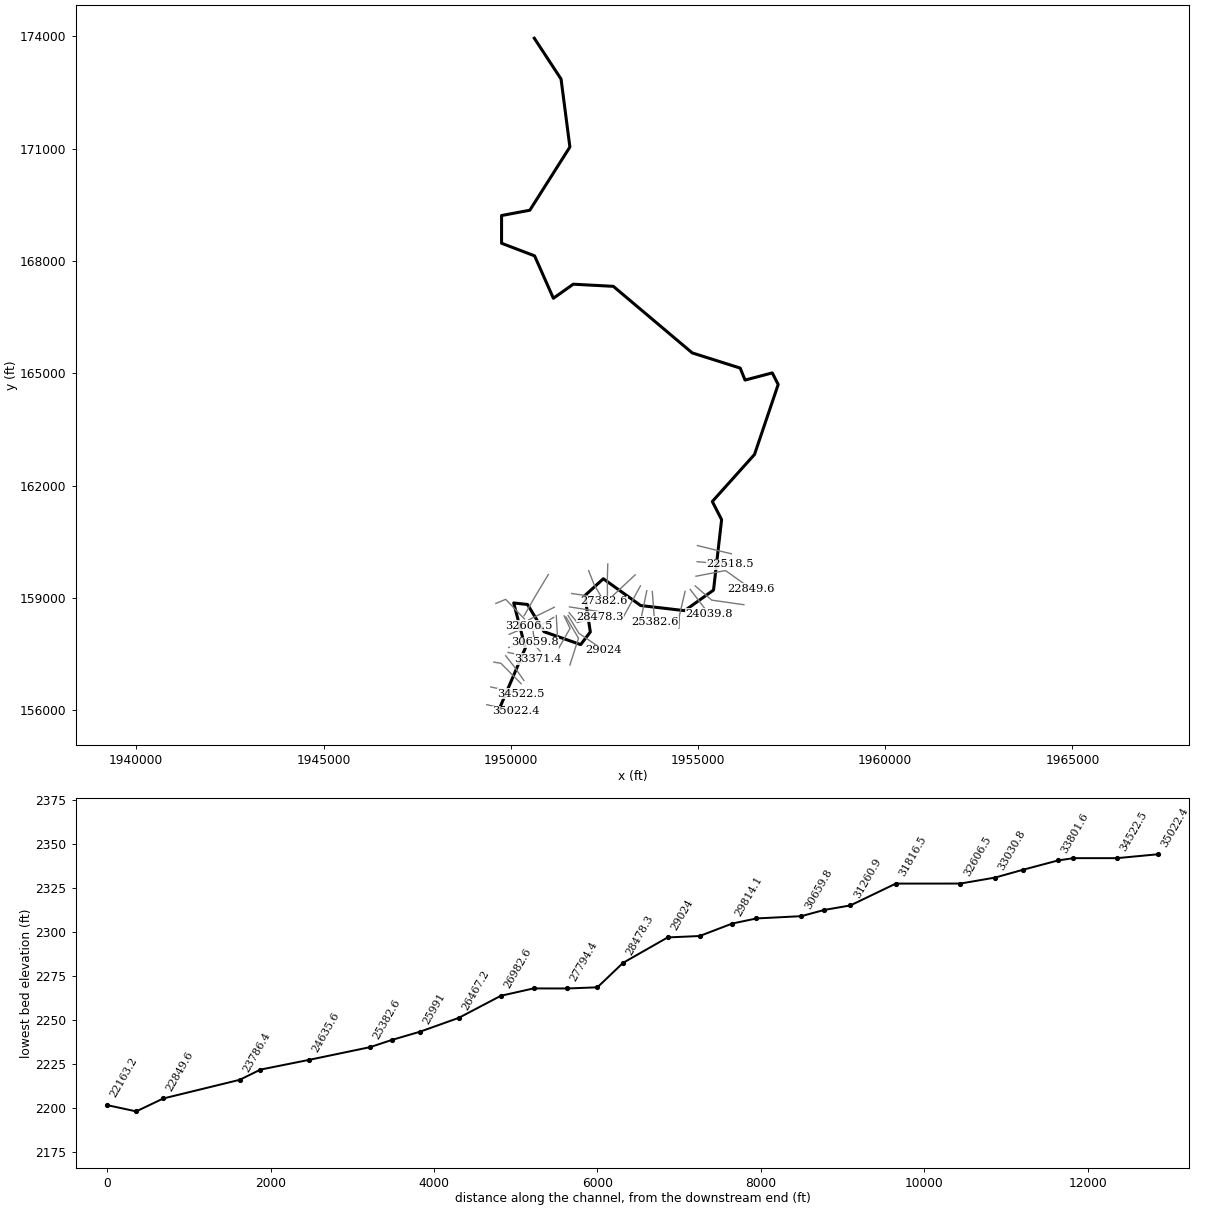
--- BrshCrk.prj (project) ---

Proj Title=BrshCrk
Current Plan=p01
Default Exp/Contr=0,0
English Units
Geom File=g01
Flow File=f01
Plan File=p01
BEGIN DESCRIPTION:
END DESCRIPTION:
DSS Export Rating Curves= 0
DSS Export Rating Curve Sorted= 0
DSS Export Volume Flow Curves= 0
DXF OffsetX= 0
DXF OffsetY= 0
DXF ScaleX= 0
DXF ScaleY= 0

--- BrshCrk.p01 (plan) ---

Plan Title=Floodplain
Program Version=4.00
Geom File=g01
Flow File=f01
K Sum by GR=0
Std Step Tol=0.01
Critical Tol=0.01
Num of Std Step Trials=20
Max Error Tol=0.3
Flow Tol Ratio=0.001
Split Flow NTrial=30
Split Flow Tol=0.02
Split Flow Ratio=0.02
Log Output Level=0
Friction Slope Method=1
Unsteady Friction Slope Method=2
Unsteady Bridges Friction Slope Method=1
Global Log Level=0
CheckData=False
Run HTab=0
Run UNet=0
Run PostProcess=0
UNET Theta=0
UNET Theta Warmup=0
UNET ZTol=0
UNET ZSATol=0
UNET MxIter=0
UNET MaxInSteps=0
UNET DtIC=0
UNET DtMin=0
UNET MaxCRTS=0
UNET WFStab=0
UNET SFStab=0
UNET WFX=0
UNET SFX=0
UNET DSS MLevel=0
UNET DZMax Abort=0
UNET Convert EG Bridges=0
UNET Use Existing IB Tables=0
UNET Froude Limit=0
UNET Froude Power=0
Write IC File=0
Echo Input=False
Echo Output=False
Write Detailed=0

--- BrshCrk.f01 (steady flow) ---

Flow Title=NFF Regression Equation
Program Version=4.00
Number of Profiles=1
Profile Names=P100yr
River Rch & RM=BrshCrk,Main      ,35022.4
6574.976
River Rch & RM=BrshCrk,Main      ,17002.1
7197.613
River Rch & RM=BrshCrk,Main      ,16281.9
8954.600
River Rch & RM=BrshCrk,Main      ,310.2
9269.585
Boundary for River Rch & Prof#=BrshCrk,Main      ,1
Up Type=0
Dn Type=3
Dn Slope=0.025631

--- BrshCrk.g01 (geometry) ---

Geom Title=USGS 3m DEM
Program Version=4.10

River Reach=BrshCrk         ,Main
Reach XY= 30
      1949673.85      155988.697     1950390.468      157664.393
      1950079.27      158866.216     1950448.911      158825.335
     1950888.619      158098.726     1951866.827      157753.953
     1952125.172      158091.925     1951978.436      159061.942
     1952472.212      159512.308     1953470.197      158797.334
     1954645.676      158660.487      1955415.34       159210.26
     1955631.353      161090.175     1955382.832      161575.299
     1956510.259      162832.362      1957141.63      164699.508
     1956983.764      165009.764     1956257.366      164818.116
     1956127.481      165138.318     1954847.213       165543.34
     1952739.498      167321.492     1951669.066      167378.216
     1951138.583      167002.408     1950637.147      168135.251
     1949755.051      168471.685     1949755.454      169212.242
     1950509.862       169353.81     1951579.433       171041.85
     1951343.721      172857.186     1950629.418      173946.419

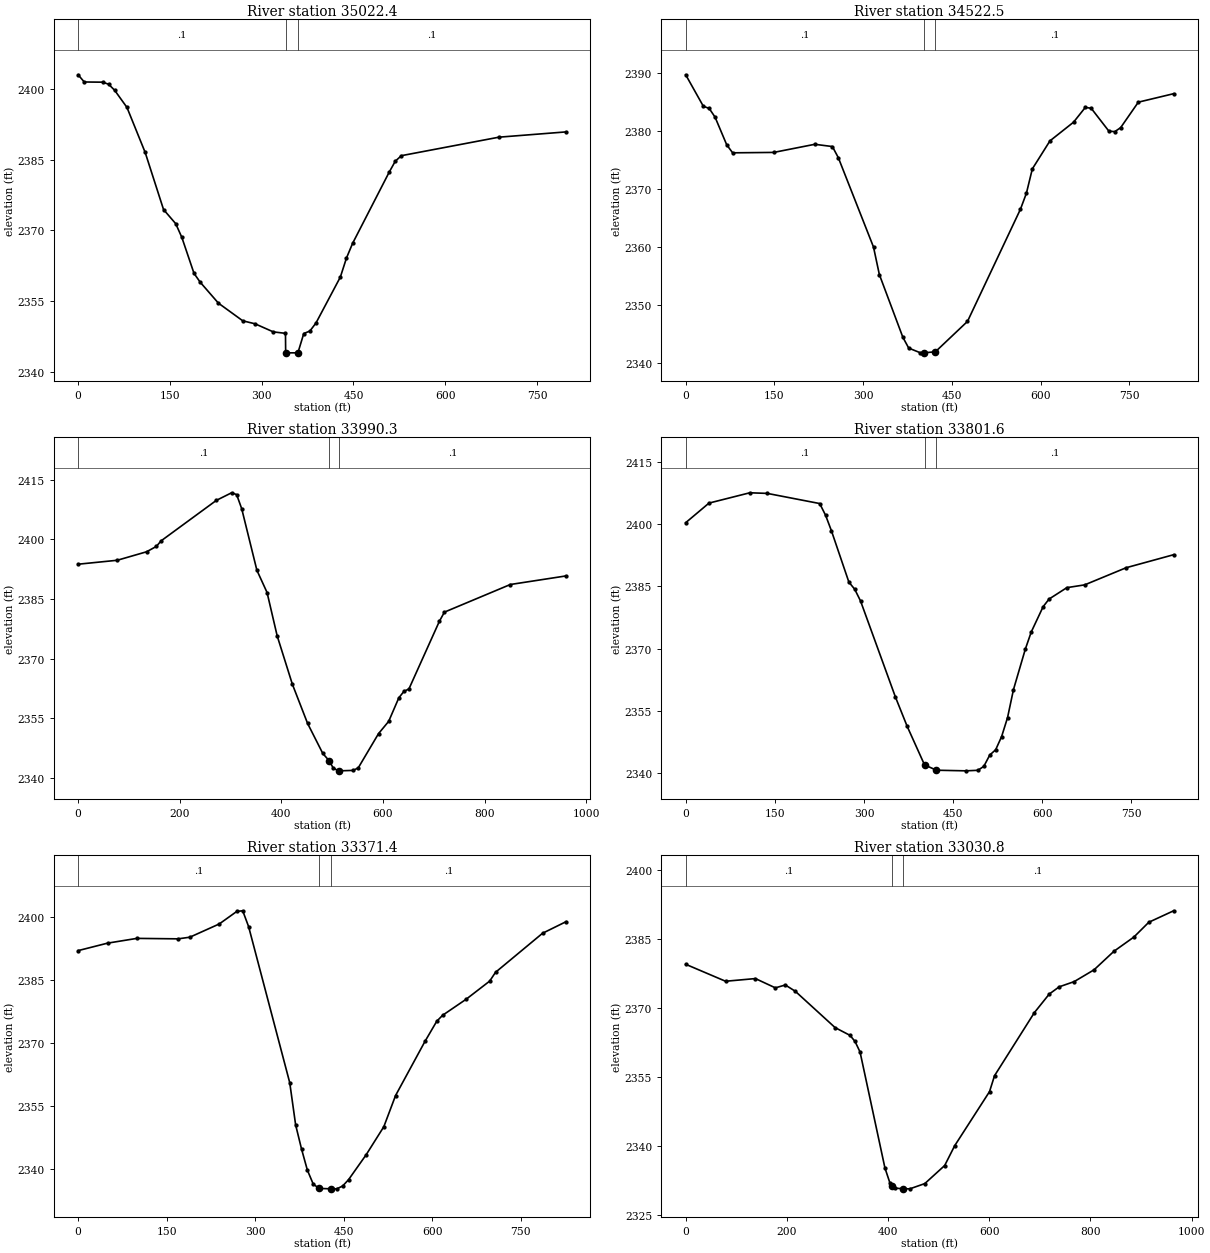
Type RM Length L Ch R = 1 ,35022.4 ,499.4,499.8,500.1
XS GIS Cut Line= 2
     1949359.169      156150.617     1950135.912      155970.032
#Sta/Elev= 30
       0 2403.05      10 2401.52    39.9 2401.48    49.8 2401.05    59.8 2399.74
    79.8 2396.12   109.6 2386.55   139.6 2374.43   159.5 2371.43   169.5 2368.52
   189.4 2360.88   199.4 2359.02   229.3 2354.55   269.1  2350.8   289.1 2350.17
     319 2348.45   338.9 2348.14   339.2    2344   359.2    2344   368.8  2348.1
   378.8 2348.63   388.8 2350.35   428.6  2360.1   438.6 2364.14   448.6 2367.25
   508.4 2382.37   518.4  2384.7   528.3 2385.87   687.8  2389.8   797.5 2390.92
#Mann= 3 , 0 , 0
       0      .1       0   339.2    .045       0   359.2      .1       0
Bank Sta=339.2,359.2
XS Rating Curve= 0 ,0
Exp/Cntr=0.3,0.1

Type RM Length L Ch R = 1 ,34522.5 ,546.9,532.2,517.7
XS GIS Cut Line= 3
     1949467.924      156621.965     1949875.441      156534.962
     1950273.949      156446.405
#Sta/Elev= 30
       0 2389.72    29.8  2384.3    39.7 2383.92    49.6 2382.43    69.4 2377.64
    79.4 2376.27   148.8 2376.34   218.3 2377.74     248 2377.35     258 2375.44
   317.5 2360.03   327.4 2355.29   367.1 2344.49     377 2342.62   396.9  2341.8
   402.1  2341.8   422.1 2341.98   476.4 2347.22     566 2366.57     576 2369.31
     586  2373.5   615.8 2378.33   655.7 2381.55   675.6  2384.1   685.5 2383.95
   715.4 2380.01   725.4 2379.92   735.3 2380.61   765.2    2385   824.9 2386.46
#Mann= 3 , 0 , 0
       0      .1       0   402.1    .045       0   422.1      .1       0
Bank Sta=402.1,422.1
XS Rating Curve= 0 ,0
Exp/Cntr=0.3,0.1

Type RM Length L Ch R = 1 ,33990.3 ,191.8,188.7,184.1
XS GIS Cut Line= 3
     1949548.533      157286.294     1949738.096      157254.256
     1950279.443      156709.581
#Sta/Elev= 30
       0 2393.72    76.9 2394.71   134.6 2396.84   153.8 2398.18   163.4  2399.6
     272 2409.76     302 2411.67   311.9 2411.22   321.9 2407.67   351.8 2392.19
   371.8 2386.61   391.7 2375.71   421.6 2363.56   451.6  2353.7   481.5 2346.16
   494.2 2344.31   501.4 2342.63   511.4  2341.8   514.2  2341.8   541.3 2341.91
   551.3 2342.56   591.2 2351.16   611.1 2354.23   631.1 2360.15     641 2361.74
     651 2362.39   710.9 2379.38   720.8 2381.68   850.5 2388.62   960.2 2390.78
#Mann= 3 , 0 , 0
       0      .1       0   494.2    .045       0   514.2      .1       0
Bank Sta=494.2,514.2
XS Rating Curve= 0 ,0
Exp/Cntr=0.3,0.1

Type RM Length L Ch R = 1 ,33801.6 ,412.5,430.1,449.2
XS GIS Cut Line= 3
     1949865.681      157456.818     1950118.713      157131.858
     1950351.617      156795.402
#Sta/Elev= 30
       0 2400.39    39.2 2405.12   107.9 2407.61   137.3 2407.46   225.5 2405.01
   235.4 2402.18   245.2 2398.45   274.6 2386.05   284.4 2384.33   294.2  2381.5
     353 2358.28   372.6 2351.26   401.9 2341.93   421.9 2340.64   471.7 2340.49
   491.7 2340.62   501.7 2341.58   511.7 2344.31   521.6 2345.58   531.6 2348.75
   541.6 2353.34   551.6 2360.12   571.5 2369.86   581.5 2374.02   601.5 2380.12
   611.5 2381.96   641.4 2384.71   671.4 2385.38   741.2 2389.52   821.1 2392.66
#Mann= 3 , 0 , 0
       0      .1       0   401.9    .045       0   421.9      .1       0
Bank Sta=401.9,421.9
XS Rating Curve= 0 ,0
Exp/Cntr=0.3,0.1

Type RM Length L Ch R = 1 ,33371.4 ,328.9,340.6,352.4
XS GIS Cut Line= 2
     1949928.088      157545.561     1950736.259      157369.658
#Sta/Elev= 30
       0 2392.06    49.8 2393.84    99.6 2394.98   169.4 2394.87   189.3 2395.26
   239.2 2398.42     269 2401.42     279 2401.57     289 2397.78   358.7 2360.53
   368.7 2350.45   378.7 2344.69   388.6 2339.65   398.6  2336.3   408.7 2335.28
   428.7  2335.2   438.5 2335.19   448.4 2335.87   458.4 2337.38   488.3 2343.34
   518.2 2350.03   538.1 2357.47   587.9 2370.38   607.9  2375.2   617.8 2376.62
   657.7 2380.45   697.6 2384.78   707.5 2386.88   787.2  2396.2   827.1 2398.97
#Mann= 3 , 0 , 0
       0      .1       0   408.7    .045       0   428.7      .1       0
Bank Sta=408.7,428.7
XS Rating Curve= 0 ,0
Exp/Cntr=0.3,0.1

Type RM Length L Ch R = 1 ,33030.8 ,420.1,424.1,428.1
XS GIS Cut Line= 3
     1949946.349        157676.1     1950557.757      157828.285
     1950783.102      157581.241
#Sta/Elev= 30
       0 2379.47    78.8 2375.79   137.8 2376.37   177.2 2374.36   196.9 2374.98
   216.6 2373.62   295.3 2365.74   324.9 2364.05   334.7 2362.73   344.6 2360.45
   393.8  2335.3   403.6 2332.07   408.7 2331.49   413.5 2330.94   428.7  2330.8
     443 2330.78   472.6 2331.92   511.9 2335.84   531.6 2340.12   600.5 2351.86
   610.4 2355.31   689.1 2368.98   718.6 2373.02   738.2 2374.58   767.8 2375.71
   807.1 2378.27   846.4 2382.29   885.8 2385.37   915.3 2388.58   964.4 2391.07
#Mann= 3 , 0 , 0
       0      .1       0   408.7    .045       0   428.7      .1       0
Bank Sta=408.7,428.7
XS Rating Curve= 0 ,0
Exp/Cntr=0.3,0.1

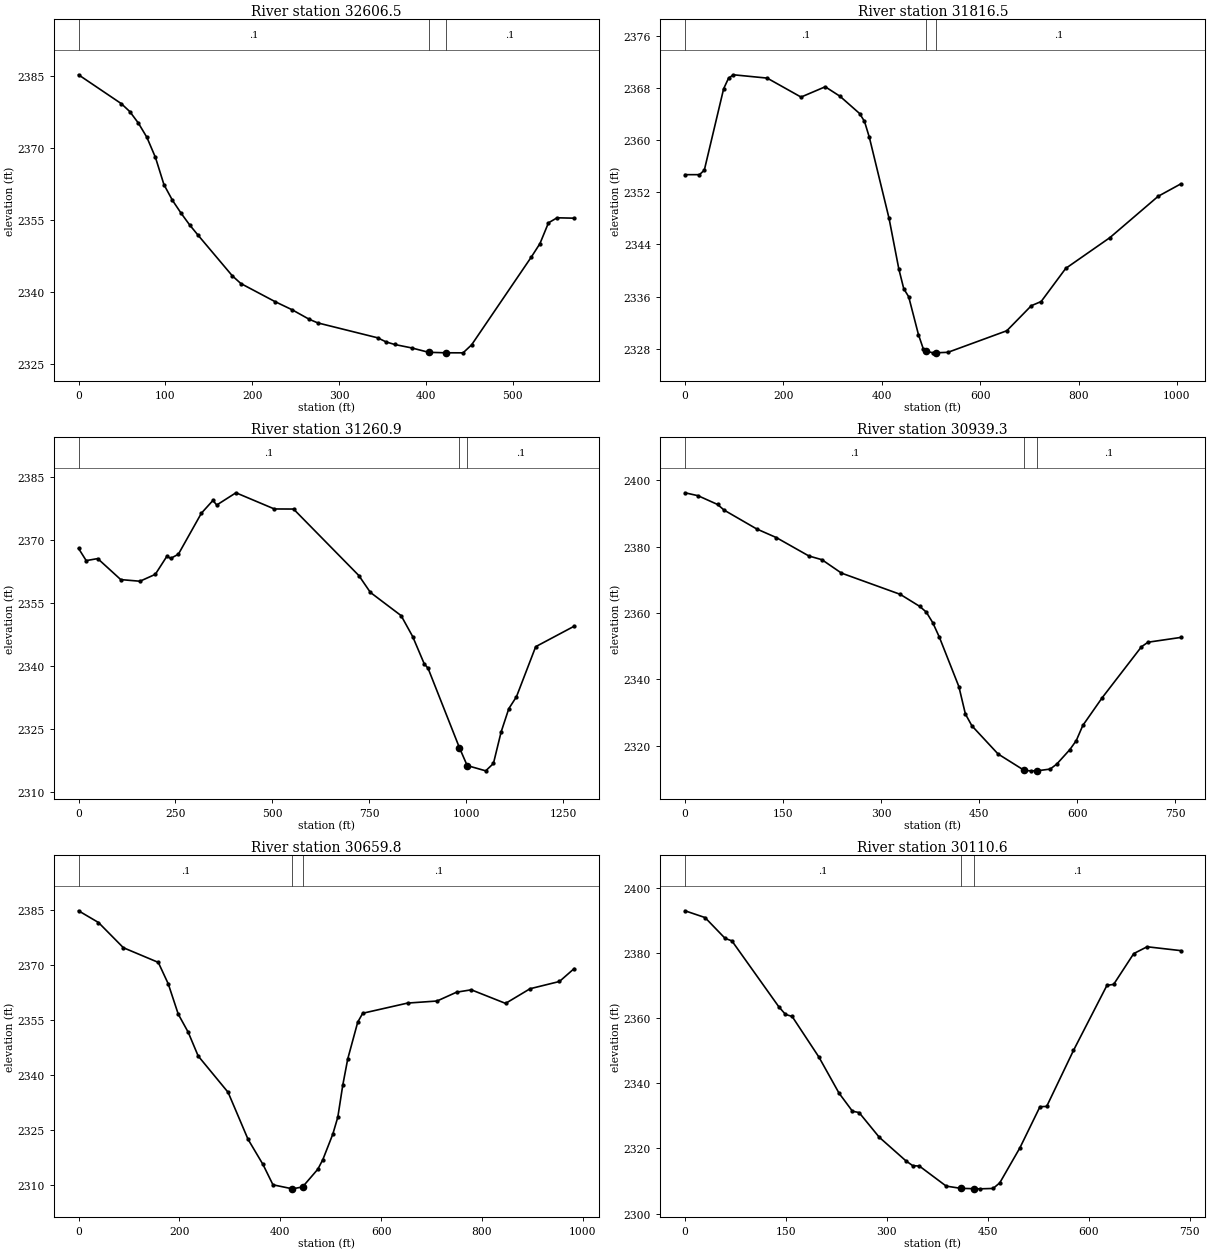
Type RM Length L Ch R = 1 ,32606.5 ,821.9,790,758.2
XS GIS Cut Line= 2
     1949960.922      158028.547     1950485.669      158252.799
#Sta/Elev= 30
       0 2385.27    49.2 2379.27      59 2377.62    68.9 2375.22    78.7 2372.26
    88.6 2368.06    98.4 2362.39   108.2 2359.13   118.1 2356.46   127.9 2354.03
   137.7 2351.87   177.1 2343.42   186.9 2341.82   226.3 2338.05     246 2336.35
   265.6 2334.38   275.5 2333.62   344.4 2330.52   354.2 2329.66     364 2329.13
   383.7 2328.41   403.1  2327.5   423.1  2327.4   442.8 2327.39   452.6 2329.05
   521.5 2347.37   531.3 2350.13   541.1 2354.45     551  2355.5   570.7 2355.42
#Mann= 3 , 0 , 0
       0      .1       0   403.1    .045       0   423.1      .1       0
Bank Sta=403.1,423.1
XS Rating Curve= 0 ,0
Exp/Cntr=0.3,0.1

Type RM Length L Ch R = 1 ,31816.5 ,587.6,555.4,523.2
XS GIS Cut Line= 4
     1949601.873      158852.009     1949864.241      158963.482
     1950319.194      158487.545     1950365.622      158443.438
#Sta/Elev= 30
       0  2354.7    29.5  2354.7    39.3 2355.39    78.6 2367.88    88.5 2369.49
    98.3 2370.02   167.1 2369.51   235.9  2366.6   285.1 2368.18     315 2366.73
   354.9 2364.08   364.9 2362.87   374.8 2360.41   414.8    2348   434.7 2340.23
   444.7  2337.2   454.7 2335.98   474.6 2330.16   484.6 2327.94   490.9 2327.61
   504.5 2327.37   510.9 2327.38   534.5 2327.45   654.2 2330.76     704  2334.6
     724 2335.24   773.9 2340.32   863.7 2345.04   961.8 2351.38  1007.5 2353.27
#Mann= 3 , 0 , 0
       0      .1       0   490.9    .045       0   510.9      .1       0
Bank Sta=490.9,510.9
XS Rating Curve= 0 ,0
Exp/Cntr=0.3,0.1

Type RM Length L Ch R = 1 ,31260.9 ,336.8,321.7,306.5
XS GIS Cut Line= 3
       1951004.4      159626.277     1950651.955      159040.917
     1950356.337      158524.688
#Sta/Elev= 30
       0 2368.06    19.8 2365.14    49.5 2365.62   108.9 2360.61   158.4 2360.22
     198 2361.86   227.8 2366.16   237.7 2365.67   257.5 2366.66   316.9 2376.45
   346.6 2379.49   356.5  2378.4     406 2381.32     505 2377.46   554.5 2377.44
   722.9 2361.58   752.7 2357.55     832 2352.01   861.7 2347.03   891.5 2340.53
   901.4 2339.46   982.3 2320.51  1002.3 2316.25  1050.1 2314.99    1070 2316.75
  1089.8 2324.25  1109.6 2329.82  1129.4 2332.67    1179 2344.61  1278.2 2349.49
#Mann= 3 , 0 , 0
       0      .1       0   982.3    .045       0  1002.3      .1       0
Bank Sta=982.3,1002.3
XS Rating Curve= 0 ,0
Exp/Cntr=0.3,0.1

Type RM Length L Ch R = 1 ,30939.3 ,276.9,279.3,281.8
XS GIS Cut Line= 2
     1951164.193      158752.187     1950484.015      158417.902
#Sta/Elev= 30
       0 2396.25    19.9 2395.37    49.9 2392.72    59.8 2391.03   109.7 2385.34
   139.6 2382.75   189.5 2377.19   209.4 2376.07   239.3 2372.03   329.1 2365.63
     359 2361.99     369 2360.27   378.9 2357.07   388.9 2352.75   418.8 2337.82
   428.8 2329.53   438.8 2325.97   478.7  2317.5   518.8 2312.54   528.5 2312.41
   538.8 2312.43   558.4 2312.94   568.4 2314.43   588.4 2318.79   598.3 2321.52
   608.3 2326.09   638.2 2334.52     698 2349.82     708 2351.19   757.9 2352.63
#Mann= 3 , 0 , 0
       0      .1       0   518.8    .045       0   538.8      .1       0
Bank Sta=518.8,538.8
XS Rating Curve= 0 ,0
Exp/Cntr=0.3,0.1

Type RM Length L Ch R = 1 ,30659.8 ,522.2,549.1,575.9
XS GIS Cut Line= 3
     1951147.943      158482.902     1950593.122      158139.331
     1950637.229       157812.01
#Sta/Elev= 30
       0 2384.76    39.6 2381.56      89 2374.68   158.2 2370.68     178 2364.81
   197.8 2356.55   217.5 2351.64   237.3 2345.14   296.6 2335.24   336.2 2322.41
   365.8 2315.55   385.6    2310   424.3  2308.9   444.3 2309.42   474.6 2314.26
   484.5 2316.87   504.3 2323.83   514.2 2328.46     524 2337.16   533.9 2344.35
   553.7 2354.38   563.6  2356.8   652.6 2359.58   710.9 2360.14   749.7 2362.55
   778.9  2363.2   846.9 2359.49   895.4 2363.49   953.7 2365.47   982.9 2368.99
#Mann= 3 , 0 , 0
       0      .1       0   424.3    .045       0   444.3      .1       0
Bank Sta=424.3,444.3
XS Rating Curve= 0 ,0
Exp/Cntr=0.3,0.1

Type RM Length L Ch R = 1 ,30110.6 ,311.1,296.6,282.6
XS GIS Cut Line= 2
     1951216.591      158526.388      1951257.05      157791.117
#Sta/Elev= 30
       0 2392.91    29.8 2390.83    59.7 2384.43    69.7 2383.68   139.3 2363.49
   149.3 2361.12   159.2 2360.49     199 2348.02   228.9 2336.95   248.8 2331.42
   258.7    2331   288.6 2323.44   328.4 2316.16   338.3 2314.72   348.3 2314.58
   388.1 2308.44   409.7 2307.75   429.7 2307.64   437.8  2307.6   457.8 2307.72
   467.7 2309.44   497.6 2320.18   527.4 2332.79   537.4 2332.89   577.2 2350.06
   626.9 2370.02   636.9 2370.33   666.7 2379.77   686.6 2381.87   736.4 2380.69
#Mann= 3 , 0 , 0
       0      .1       0   409.7    .045       0   429.7      .1       0
Bank Sta=409.7,429.7
XS Rating Curve= 0 ,0
Exp/Cntr=0.3,0.1

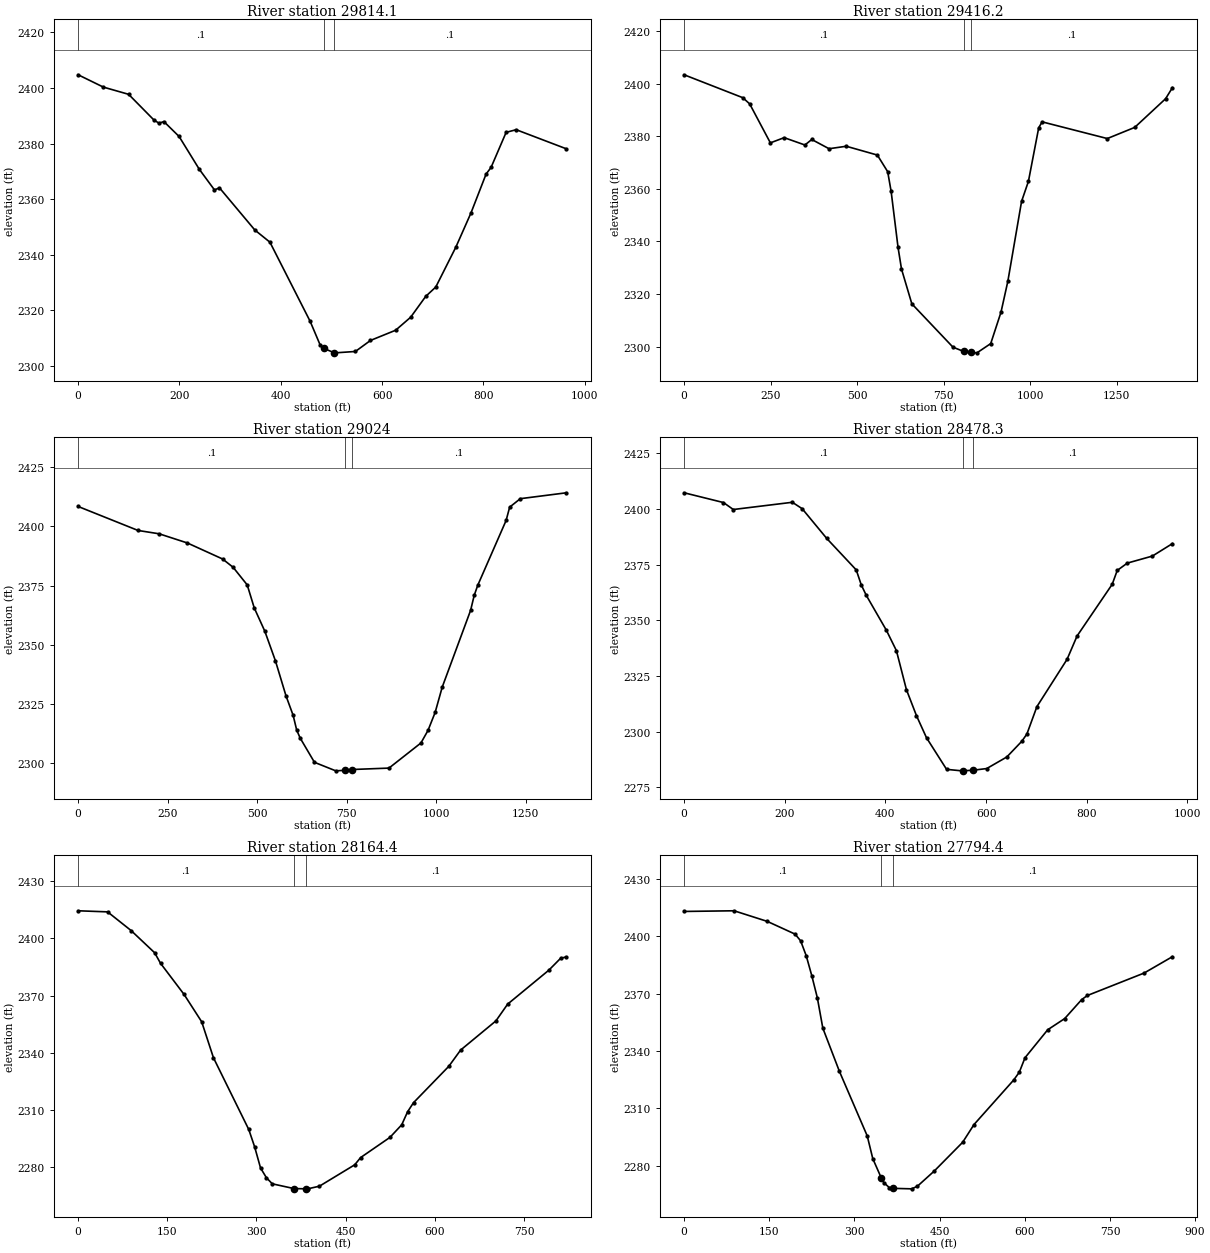
Type RM Length L Ch R = 1 ,29814.1 ,392.5,397.8,402.6
XS GIS Cut Line= 3
     1951425.539      158520.821     1951584.371      158188.081
     1951288.359      157671.597
#Sta/Elev= 30
       0 2404.77    49.8 2400.33    99.6 2397.74   149.5 2388.51   159.4 2387.37
   169.4 2387.91   199.3 2382.56   239.2 2370.75   269.1 2363.34     279 2364.08
   348.8  2348.9   378.6 2344.52     458 2316.04   477.8 2307.51   484.5 2306.32
   504.5 2304.82   507.6  2304.7   547.3 2305.19   577.1 2309.16   626.7 2312.83
   656.4 2317.51   686.2 2325.03     706 2328.38   745.7 2342.76   775.5 2355.05
   805.3 2369.03   815.2 2371.45   844.9 2384.06   864.8    2385     964 2378.11
#Mann= 3 , 0 , 0
       0      .1       0   484.5    .045       0   504.5      .1       0
Bank Sta=484.5,504.5
XS Rating Curve= 0 ,0
Exp/Cntr=0.3,0.1

Type RM Length L Ch R = 1 ,29416.2 ,360.1,392,423.4
XS GIS Cut Line= 3
      1951473.69      158491.862     1951809.549       157925.76
     1951579.728       157208.44
#Sta/Elev= 30
       0 2403.42   169.6  2394.7   189.5 2392.34   249.3 2377.52   289.2  2379.5
   349.1 2376.71     369  2378.8   418.9 2375.29   468.7 2376.23   558.5 2372.88
   588.4 2366.55   598.4 2359.02   618.3 2337.79   628.3 2329.54   658.2 2316.29
   777.2 2299.78   808.1 2298.18   828.1 2297.82   846.5 2297.64   886.2 2301.16
   915.9  2313.1   935.7 2324.85   975.4 2355.26   995.2 2362.87  1024.9 2383.25
  1034.8 2385.51  1223.2 2379.16  1302.4  2383.4  1391.6  2394.3  1411.5 2398.53
#Mann= 3 , 0 , 0
       0      .1       0   808.1    .045       0   828.1      .1       0
Bank Sta=808.1,828.1
XS Rating Curve= 0 ,0
Exp/Cntr=0.3,0.1

Type RM Length L Ch R = 1 ,29024   ,523.7,545.8,568.4
XS GIS Cut Line= 3
     1951533.083       158529.28     1951818.835      158058.081
     1952489.727      157598.439
#Sta/Elev= 30
       0  2408.4   167.3 2398.28   226.3 2396.87   305.1    2393   403.5 2386.24
     433 2382.73   472.4 2375.29     492 2365.59   521.6 2355.74   551.1  2343.3
   580.8 2328.44   600.7 2320.24   610.6 2314.02   620.5 2310.61   660.2 2300.43
   719.7 2296.83   745.2 2297.05   765.2 2297.39   868.4 2297.99   957.7 2308.59
   977.5  2313.9   997.4 2321.48  1017.2 2332.17  1096.5 2364.57  1106.5 2370.86
  1116.4 2375.13  1195.7 2402.51  1205.6 2408.12  1235.4 2411.69  1364.3 2414.18
#Mann= 3 , 0 , 0
       0      .1       0   745.2    .045       0   765.2      .1       0
Bank Sta=745.2,765.2
XS Rating Curve= 0 ,0
Exp/Cntr=0.3,0.1

Type RM Length L Ch R = 1 ,28478.3 ,323.7,314,304.2
XS GIS Cut Line= 3
     1951558.625      158606.795     1951777.049      158343.617
     1952386.001      158498.319
#Sta/Elev= 30
       0 2407.35    78.2 2402.96    97.7 2399.83     215 2403.08   234.5 2400.21
   283.4 2386.83     342 2372.69     352 2365.95     362 2361.23   401.8 2345.61
   421.8 2336.42   441.7  2318.9   461.7 2307.19   481.6 2297.28   521.5 2283.08
   551.4 2282.41   554.4 2282.43   574.4 2282.69   601.3 2283.44   641.2 2288.64
   671.1 2295.72   681.1 2298.96     701 2311.27   760.9 2332.51   780.8 2343.01
   850.6 2366.23   860.6 2372.46   880.6 2375.75   930.4 2378.91   970.3 2384.52
#Mann= 3 , 0 , 0
       0      .1       0   554.4    .045       0   574.4      .1       0
Bank Sta=554.4,574.4
XS Rating Curve= 0 ,0
Exp/Cntr=0.3,0.1

Type RM Length L Ch R = 1 ,28164.4 ,368.6,369.9,371.3
XS GIS Cut Line= 2
     1951569.471      158760.915     1952380.783      158632.247
#Sta/Elev= 30
       0 2414.55    49.5 2413.98    89.1 2404.16   128.7  2392.5   138.6 2386.96
   178.2 2370.62   207.8 2356.26   227.6 2337.37     287  2299.7   296.9 2290.56
   306.8  2279.5   316.7 2274.36   326.6 2271.16   362.9 2268.68   382.9 2268.54
     386 2268.53   405.8 2269.91   465.2 2281.15   475.1 2284.94   524.5 2295.56
   544.3 2302.17   554.2 2309.03   564.1 2313.77   623.5 2332.88   643.3 2341.39
   702.7 2356.72   722.5 2365.54   791.8 2383.37   811.6 2389.62   821.4 2390.33
#Mann= 3 , 0 , 0
       0      .1       0   362.9    .045       0   382.9      .1       0
Bank Sta=362.9,382.9
XS Rating Curve= 0 ,0
Exp/Cntr=0.3,0.1

Type RM Length L Ch R = 1 ,27794.4 ,439.5,411.8,387.9
XS GIS Cut Line= 3
     1951628.666      159118.236      1952025.31        159061.4
     1952424.253      158833.612
#Sta/Elev= 30
       0  2413.1      88 2413.45   146.6 2407.88   195.5 2401.22   205.2 2397.72
     215 2389.97   224.8 2379.53   234.6 2367.94   244.3 2352.01   273.6 2329.32
   322.5  2295.6   332.3 2283.69   347.6 2273.35   351.8 2271.09   361.6  2268.5
   367.6 2268.14   400.7 2267.88   410.7 2269.19   440.6 2277.21   490.6 2292.25
   510.6 2301.55   580.5 2324.86   590.4 2328.96   600.4 2336.51   640.4 2351.16
   670.3 2357.01   700.3 2366.97   710.3  2369.1   810.2 2380.85   860.1 2389.43
#Mann= 3 , 0 , 0
       0      .1       0   347.6    .045       0   367.6      .1       0
Bank Sta=347.6,367.6
XS Rating Curve= 0 ,0
Exp/Cntr=0.3,0.1

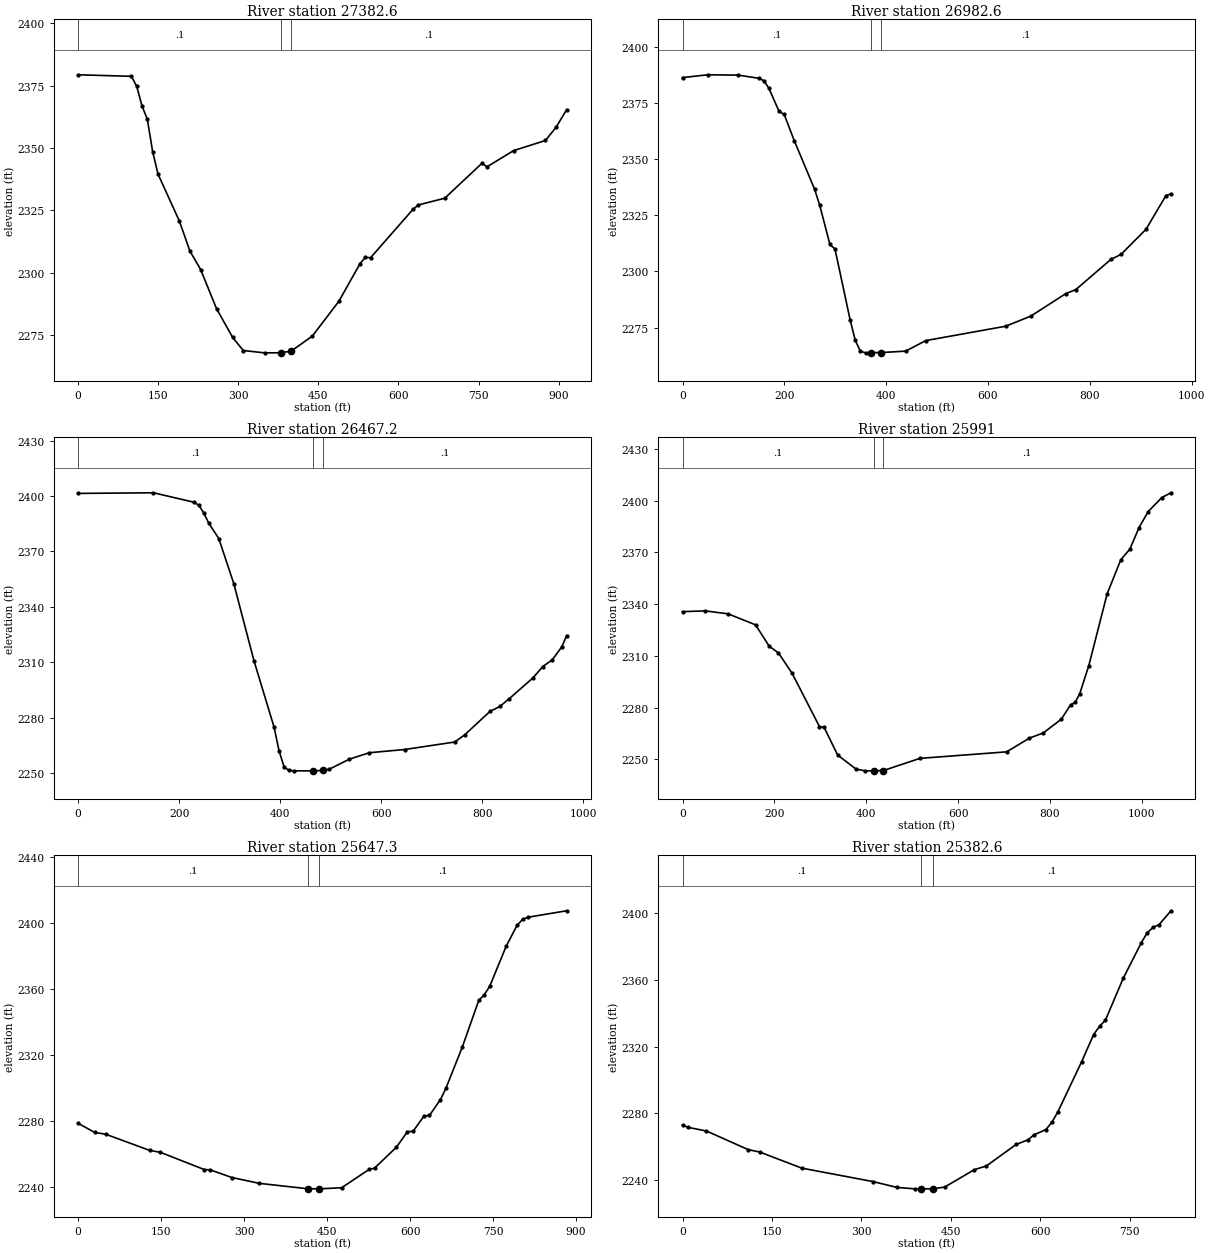
Type RM Length L Ch R = 1 ,27382.6 ,410.1,399.9,386.8
XS GIS Cut Line= 3
     1952079.672      159728.684     1952221.996      159366.704
     1952485.923      158911.798
#Sta/Elev= 30
       0 2379.36    99.7 2378.74   109.7 2374.72   119.7  2366.8   129.6 2361.52
   139.6 2348.46   149.6 2339.53   189.5 2320.77   209.4 2308.68   229.4 2301.29
   259.3 2285.56   289.2 2274.15   309.2 2268.83   349.1  2267.9     379 2267.92
     399 2268.58   438.6 2274.62   488.2 2288.52   527.9 2303.63   537.8 2306.15
   547.7 2306.03   627.1 2325.41     637 2327.18   686.6 2329.88   756.1 2343.84
     766  2342.5   815.6 2348.96   875.2 2353.02     895 2358.29   914.9 2365.35
#Mann= 3 , 0 , 0
       0      .1       0     379    .045       0     399      .1       0
Bank Sta=379,399
XS Rating Curve= 0 ,0
Exp/Cntr=0.3,0.1

Type RM Length L Ch R = 1 ,26982.6 ,531.8,515.3,497.9
XS GIS Cut Line= 3
     1952591.886      159906.943     1952579.474      159527.788
     1952583.041      158947.798
#Sta/Elev= 30
       0 2386.35    49.9  2387.6   109.8 2387.44   149.8 2386.05   159.7 2384.96
   169.7 2381.55   189.7 2371.27   199.7 2369.92   219.6 2358.19   259.6  2336.5
   269.5 2329.45   289.5 2312.02   299.5 2309.95   329.4 2278.21   339.4 2269.24
   349.4 2264.47   359.4 2263.73   369.4 2263.83   389.4 2263.84   438.3 2264.49
   477.7 2269.18     635  2275.6   684.1  2280.1   752.9 2290.12   772.6 2291.93
   841.4 2305.35     861 2307.55   910.2 2318.72   949.5 2333.77   959.4 2334.59
#Mann= 3 , 0 , 0
       0      .1       0   369.4    .045       0   389.4      .1       0
Bank Sta=369.4,389.4
XS Rating Curve= 0 ,0
Exp/Cntr=0.3,0.1

Type RM Length L Ch R = 1 ,26467.2 ,471.6,476.3,480.9
XS GIS Cut Line= 3
     1953324.067      159617.282     1952720.669      159053.932
     1952679.279      158918.197
#Sta/Elev= 30
       0 2401.38   149.2 2401.72   228.8 2396.64   238.7 2395.08   248.6 2390.88
   258.6  2385.3   278.5 2376.96   308.3 2352.49   348.1 2310.91   387.9 2274.95
   397.8 2262.18   407.8  2253.3   417.7  2251.4   427.7  2251.2   465.7  2251.2
   485.7 2251.41   497.3 2252.08   537.1 2257.52   576.9 2261.01   646.5 2262.74
   745.9 2266.81   765.8 2270.75   815.6 2283.37     835 2286.04   853.9 2290.29
   901.2 2301.63   920.1 2307.64     939 2311.31     958 2318.37   967.4 2324.38
#Mann= 3 , 0 , 0
       0      .1       0   465.7    .045       0   485.7      .1       0
Bank Sta=465.7,485.7
XS Rating Curve= 0 ,0
Exp/Cntr=0.3,0.1

Type RM Length L Ch R = 1 ,25991   ,336.1,343.6,351.1
XS GIS Cut Line= 2
     1953462.902      159320.923     1952950.281      158389.126
#Sta/Elev= 30
       0  2335.6    49.7 2336.05    99.4 2334.31     159 2327.97   188.8 2315.52
   208.7 2311.74   238.5 2299.93   298.2 2268.95   308.1 2268.61   337.9 2252.42
   377.7 2244.35   397.6 2243.32   417.1 2243.36   437.1 2243.47   516.8 2250.55
   705.7 2254.33   755.4 2262.31   785.2 2265.24     825 2273.31   844.8  2281.6
   854.8 2283.02   864.7 2287.91   884.6 2304.34   924.4 2345.85   954.2 2365.65
     974 2371.85   993.9 2384.33  1013.8  2393.6  1043.6 2401.77  1063.5 2404.51
#Mann= 3 , 0 , 0
       0      .1       0   417.1    .045       0   437.1      .1       0
Bank Sta=417.1,437.1
XS Rating Curve= 0 ,0
Exp/Cntr=0.3,0.1

Type RM Length L Ch R = 1 ,25647.3 ,257.7,264.7,271.7
XS GIS Cut Line= 2
     1953633.573      159192.296     1953454.892      158327.719
#Sta/Elev= 30
       0 2278.46    29.8 2272.94    49.6 2271.87     129 2262.05   148.8 2260.83
   228.2 2250.34   238.1 2250.24   277.8 2245.55   327.4 2241.99   414.8 2238.72
   434.8 2238.66   476.1 2239.31   525.7 2250.42   535.7 2251.27   575.3    2264
   595.2 2273.45   605.1 2273.51   624.9 2282.84   634.9 2283.25   654.7 2292.86
   664.6 2299.71   694.4 2324.92   724.1 2353.25     734  2356.6     744 2361.88
   773.7 2386.18   793.6 2399.01   803.5 2402.44   813.4 2403.74   882.8 2407.62
#Mann= 3 , 0 , 0
       0      .1       0   414.8    .045       0   434.8      .1       0
Bank Sta=414.8,434.8
XS Rating Curve= 0 ,0
Exp/Cntr=0.3,0.1

Type RM Length L Ch R = 1 ,25382.6 ,754.8,747.1,739.4
XS GIS Cut Line= 3
     1953780.578      159172.466     1953811.203      158764.113
     1953841.829      158355.759
#Sta/Elev= 30
       0 2272.82      10 2271.45      40 2269.34   109.9 2258.17   129.8 2256.66
   199.8 2247.05   319.6 2238.94   359.6 2235.45   389.5  2234.6   399.5  2234.6
   419.5 2234.62   439.5 2235.66   489.4 2246.13   509.4 2248.32   559.3 2261.23
   579.3 2264.03   589.3 2267.01   609.3 2270.19   619.2  2274.5   629.2 2280.73
   669.2 2310.93   689.2 2327.17   699.2 2332.17   709.1 2335.88   739.1 2361.16
   769.1 2382.25     779  2388.3     789 2391.57     799 2393.21     819 2401.54
#Mann= 3 , 0 , 0
       0      .1       0   399.5    .045       0   419.5      .1       0
Bank Sta=399.5,419.5
XS Rating Curve= 0 ,0
Exp/Cntr=0.3,0.1

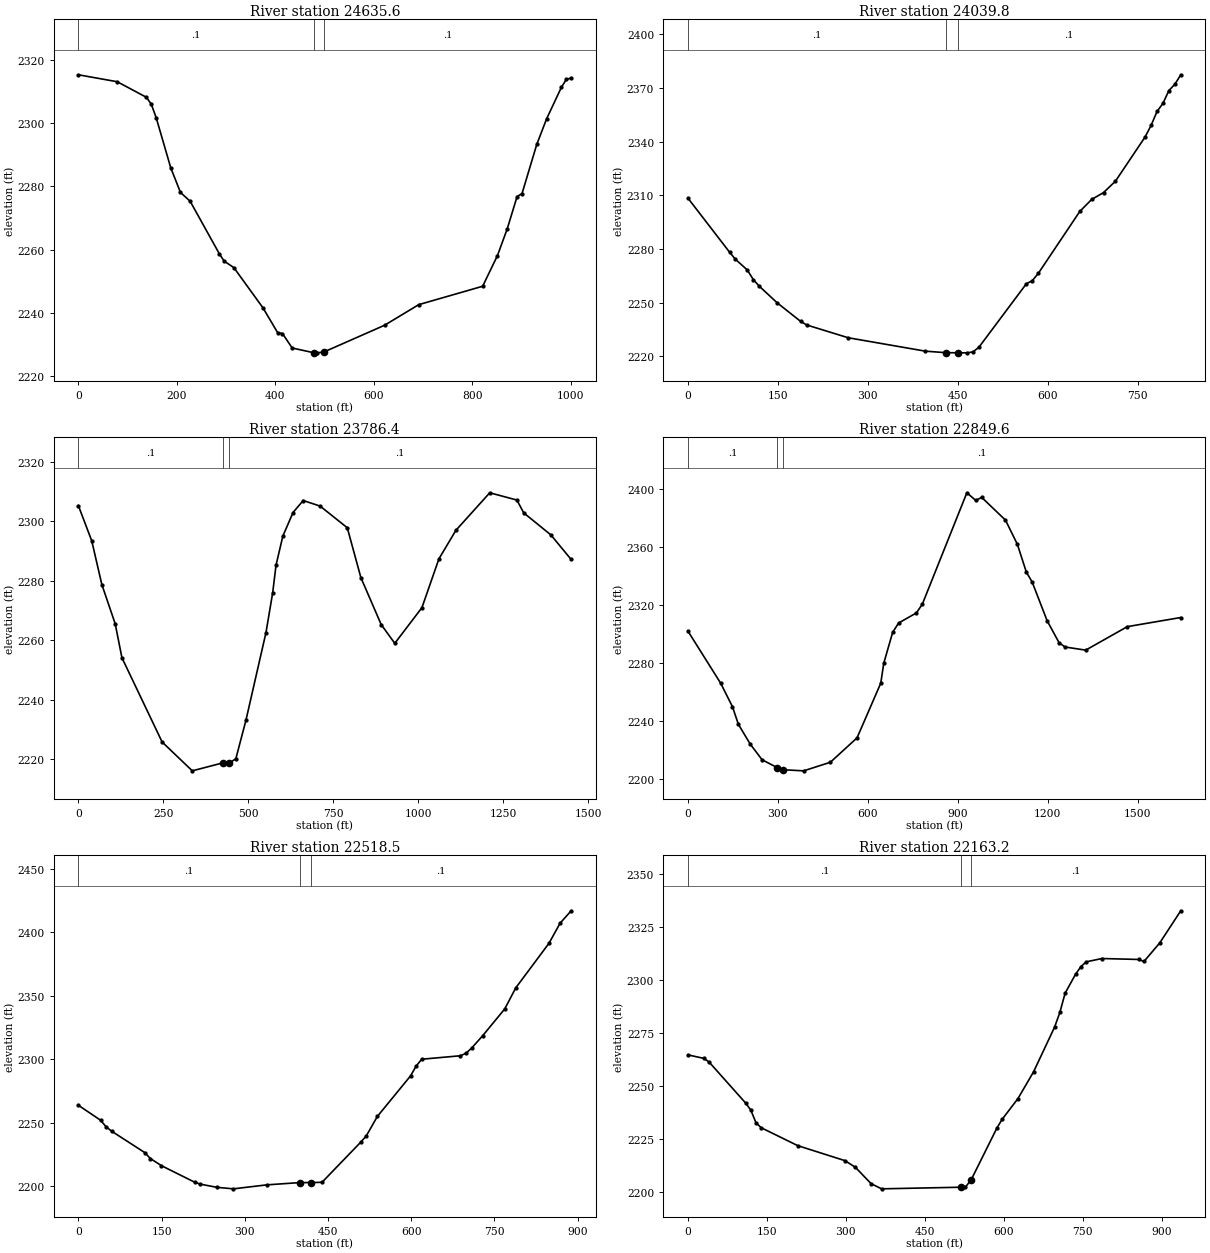
Type RM Length L Ch R = 1 ,24635.6 ,573.2,595.4,617.6
XS GIS Cut Line= 3
     1954656.349      159174.078     1954504.414      158530.702
     1954490.815      158191.554
#Sta/Elev= 30
       0 2315.32    78.9 2313.12   138.1  2308.2     148 2306.03   157.9 2301.78
   187.5 2285.93   207.2 2278.12   226.9 2275.33   286.1 2258.73     296 2256.38
   315.7 2254.33   374.9 2241.58   404.5 2233.78   414.4 2233.48   434.1 2228.91
   477.7 2227.42   483.5 2227.38   497.7  2227.6   621.6  2236.1     691 2242.62
   820.8 2248.44   850.8 2258.14   870.7 2266.61   890.7 2276.82   900.7 2277.74
   930.6 2293.28   950.6 2301.38   980.5 2311.32   990.5 2313.83  1000.5 2314.32
#Mann= 3 , 0 , 0
       0      .1       0   477.7    .045       0   497.7      .1       0
Bank Sta=477.7,497.7
XS Rating Curve= 0 ,0
Exp/Cntr=0.3,0.1

Type RM Length L Ch R = 1 ,24039.8 ,248.2,253.4,258.6
XS GIS Cut Line= 2
      1954791.77      159227.637     1955290.851      158574.785
#Sta/Elev= 30
       0 2308.35    69.3 2278.17    79.2 2274.15      99 2268.18   108.9 2262.84
   118.8 2259.16   148.5  2249.9   188.1 2239.38     198 2237.43   267.3 2230.28
     396 2222.78   429.6 2221.95   449.6 2221.88   465.3 2221.85   475.2 2222.36
   485.1 2224.95   564.3 2260.48   574.2 2262.21   584.2 2266.28   653.4 2300.92
   673.2 2307.64     693 2311.47   712.9 2317.87   762.4 2342.62   772.3 2349.05
   782.2 2356.83   792.1 2361.38     802 2368.54   811.9 2372.03   821.8 2377.35
#Mann= 3 , 0 , 0
       0      .1       0   429.6    .045       0   449.6      .1       0
Bank Sta=429.6,449.6
XS Rating Curve= 0 ,0
Exp/Cntr=0.3,0.1

Type RM Length L Ch R = 1 ,23786.4 ,910.9,935.6,960.4
XS GIS Cut Line= 3
     1954926.009      159320.923     1955366.852      158941.722
     1956226.252      158818.981
#Sta/Elev= 30
       0 2305.25    39.4 2293.39      69 2278.72   108.4 2265.49   128.1  2254.1
   246.4 2225.75   335.1 2216.06   424.3 2218.72   444.3 2218.71   463.2 2220.13
   492.8 2233.02   551.9 2262.58   571.6 2275.98   581.5 2285.25   601.4 2294.97
   631.4 2302.93   661.3 2306.97   711.2 2305.08     791 2297.81     831 2281.04
   890.8 2265.24   930.7 2258.94  1010.6 2270.94  1060.5 2287.34  1110.4 2296.93
  1210.1 2309.57    1290 2307.12  1309.9 2302.82  1389.7 2295.42  1449.6 2287.14
#Mann= 3 , 0 , 0
       0      .1       0   424.3    .045       0   444.3      .1       0
Bank Sta=424.3,444.3
XS Rating Curve= 0 ,0
Exp/Cntr=0.3,0.1

Type RM Length L Ch R = 1 ,22849.6 ,337.4,330.6,323.8
XS GIS Cut Line= 3
     1954947.368      159579.903     1955734.546      159731.716
     1956421.155      159243.495
#Sta/Elev= 30
       0 2301.91   108.9 2266.07   148.5 2249.73   168.2 2237.58   207.8 2223.91
   247.4 2213.09   297.8  2207.7   317.8 2206.22     386 2205.47   475.1 2211.39
   564.2 2228.26   643.3 2266.04   653.2 2279.71   682.9 2301.07   702.7 2307.53
   762.1 2314.49   781.9 2320.54   930.5 2397.46   960.3 2392.17   980.1 2394.26
  1059.4 2378.56    1099 2361.89  1128.8 2342.78  1148.6 2335.74  1198.2 2309.15
  1237.8 2294.08  1257.6 2290.99    1327 2288.81  1465.8 2305.03  1644.2 2311.34
#Mann= 3 , 0 , 0
       0      .1       0   297.8    .045       0   317.8      .1       0
Bank Sta=297.8,317.8
XS Rating Curve= 0 ,0
Exp/Cntr=0.3,0.1

Type RM Length L Ch R = 1 ,22518.5 ,359.9,355.6,351.6
XS GIS Cut Line= 2
     1954977.204      159967.639     1955863.145      159900.292
#Sta/Elev= 30
       0 2263.86    39.9 2252.14    49.9 2246.99    59.9  2243.5   119.8 2226.62
   129.8 2221.99   149.8 2216.36   209.6 2203.38   219.6 2201.86   249.6 2199.35
   279.5 2198.15   339.4 2201.26   399.8 2203.09   419.8 2203.05   439.3 2203.31
   509.1 2234.85   519.1 2239.77   539.1 2255.11     599 2287.02     609 2294.69
     619 2300.06   688.8 2302.79   698.8 2304.74   708.8 2308.73   728.8 2318.48
   768.7 2339.62   788.7 2356.24   848.6  2391.3   868.5 2407.02   888.5 2416.78
#Mann= 3 , 0 , 0
       0      .1       0   399.8    .045       0   419.8      .1       0
Bank Sta=399.8,419.8
XS Rating Curve= 0 ,0
Exp/Cntr=0.3,0.1

Type RM Length L Ch R = 1 ,22163.2 ,406.1,411.3,416.2
XS GIS Cut Line= 3
     1954984.747      160399.564       1955496.3      160272.613
     1955895.113       160179.72
#Sta/Elev= 30
       0 2264.82    29.8  2263.2    39.8 2261.55   109.4 2242.19   119.3 2238.88
   129.3 2232.84   139.2 2230.49   208.8 2222.04   298.3 2214.99   318.2 2211.85
   348.1 2204.13     368  2201.7   518.3 2202.46   527.1 2202.45   538.3 2205.98
     587 2230.28     597 2234.44     627 2244.17   656.9 2256.88   696.9 2277.98
   706.8 2284.83   716.8 2293.91   736.8  2302.9   746.8 2306.42   756.8 2308.66
   786.8 2310.23   856.7 2309.79   866.6 2308.83   896.6 2317.57   936.6 2332.73
#Mann= 3 , 0 , 0
       0      .1       0   518.3    .045       0   538.3      .1       0
Bank Sta=518.3,538.3
XS Rating Curve= 0 ,0
Exp/Cntr=0.3,0.1