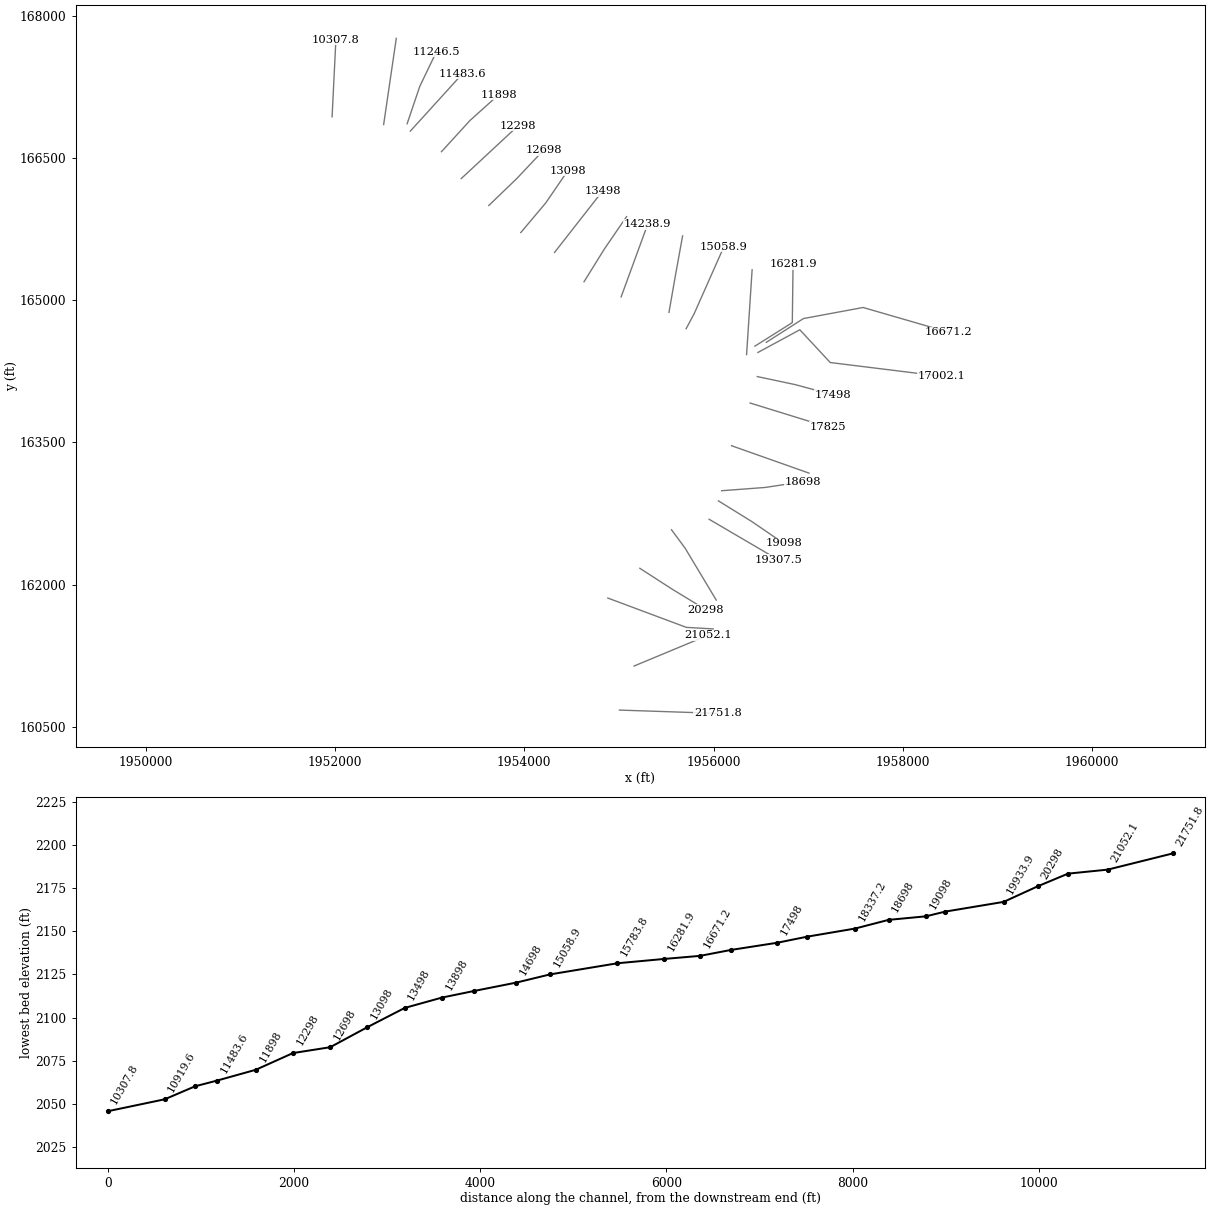
HEC-RAS study BrshCrk.prj: BrshCrk

--- BrshCrk.g01 (geometry) --- (continued)

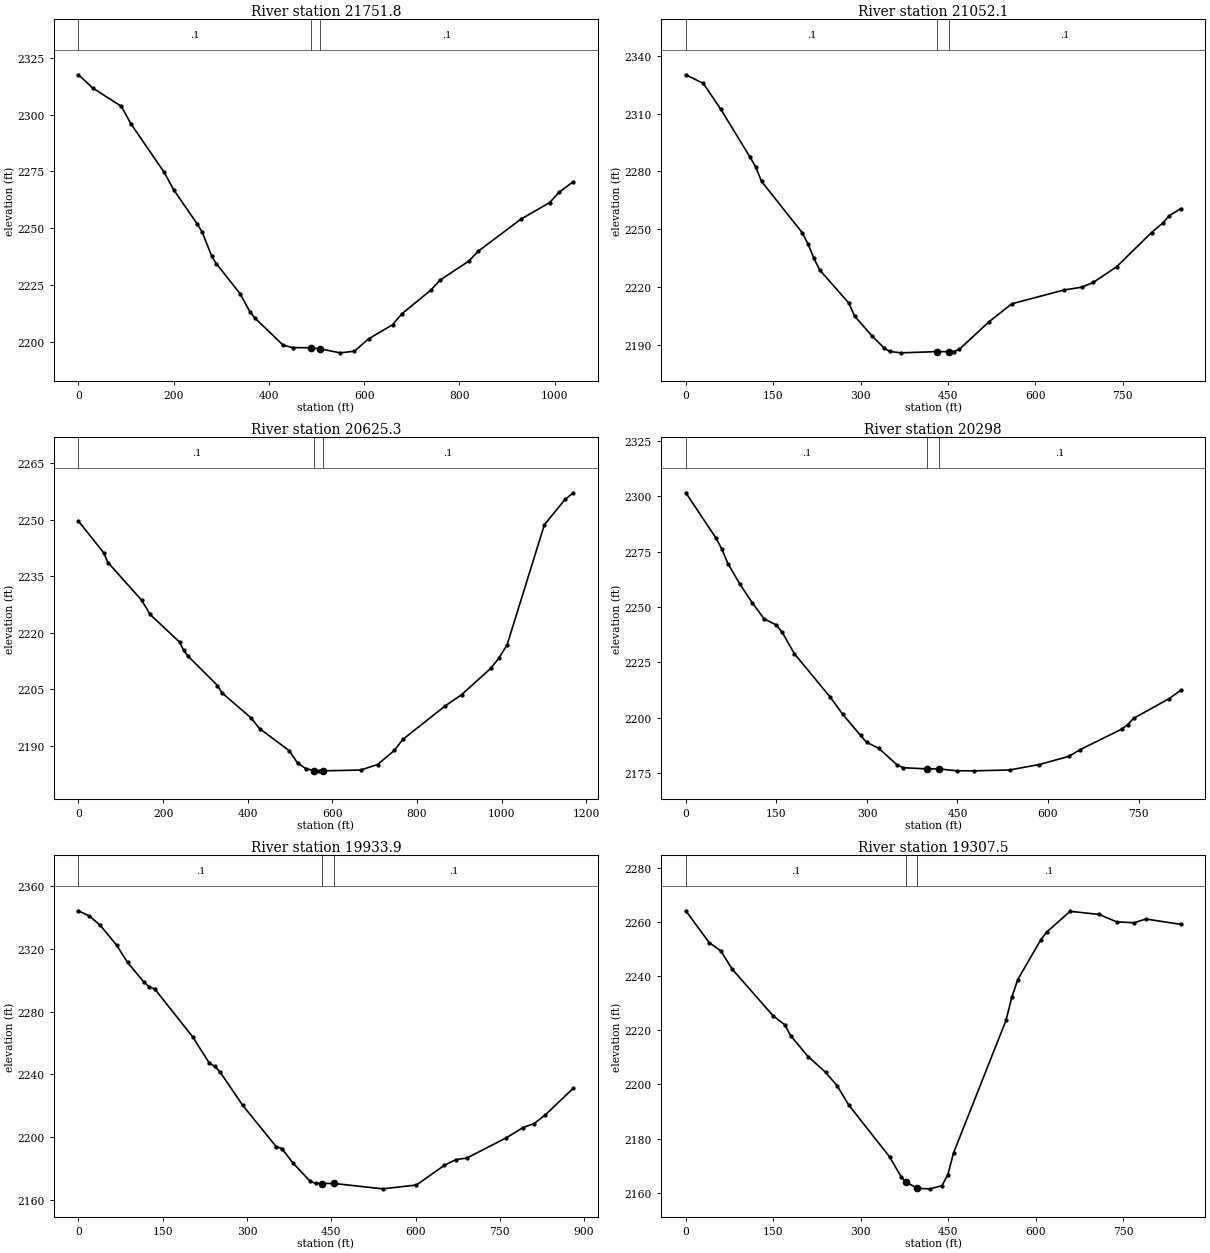
Type RM Length L Ch R = 1 ,21751.8 ,689.5,699.9,710.3
XS GIS Cut Line= 2
     1955006.106      160674.564     1956044.698      160639.855
#Sta/Elev= 30
       0 2317.56      30 2311.71    89.9  2303.7   109.9 2296.07   179.9 2274.62
   199.8 2266.98   249.8 2251.74   259.8 2248.24   279.8 2237.71   289.8  2234.3
   339.7 2221.09   359.7 2213.32   369.7  2210.6   429.7 2198.52   449.6 2197.43
   487.6 2197.35   507.6 2196.86   549.6 2195.12   579.5 2195.85   609.5 2201.32
   659.5 2207.49   679.5 2212.38   739.4 2222.62   759.4 2227.16   819.4 2235.46
   839.3 2239.84   929.3 2254.01   989.2 2261.23  1009.2 2265.77  1039.2 2270.54
#Mann= 3 , 0 , 0
       0      .1       0   487.6    .045       0   507.6      .1       0
Bank Sta=487.6,507.6
XS Rating Curve= 0 ,0
Exp/Cntr=0.3,0.1

Type RM Length L Ch R = 1 ,21052.1 ,445.4,426.3,407.1
XS GIS Cut Line= 2
     1955160.465      161139.596     1955944.661      161465.686
#Sta/Elev= 30
       0 2330.18      30 2325.69      60 2312.26   109.9 2287.54   119.9 2282.33
   129.9  2274.8   199.8 2248.11   209.8 2242.23   219.8 2234.83   229.8 2228.76
   279.8 2211.52   289.8 2204.76   319.7 2194.45   339.7 2188.41   349.7 2186.43
   369.7 2185.72   431.6 2186.36   451.6 2186.35   459.6 2186.36   469.6 2187.61
   519.6 2201.65   559.5 2211.22   649.5  2218.4   679.4 2219.81   699.4 2222.34
   739.4 2230.44   799.3 2248.23   819.3 2253.33   829.3 2256.86   849.3 2260.62
#Mann= 3 , 0 , 0
       0      .1       0   431.6    .045       0   451.6      .1       0
Bank Sta=431.6,451.6
XS Rating Curve= 0 ,0
Exp/Cntr=0.3,0.1

Type RM Length L Ch R = 1 ,20625.3 ,332.5,327.1,322.3
XS GIS Cut Line= 3
      1954883.29      161857.331      1955713.63      161547.622
      1955996.64      161531.603
#Sta/Elev= 30
       0 2249.64    59.8 2241.22    69.7 2238.67   149.4 2228.66   169.3 2224.89
     239 2217.55   248.9 2215.33   258.9 2213.84   328.6 2206.04   338.6 2204.17
   408.3  2197.4   428.2  2194.6   497.9 2188.77   517.8 2185.49   537.7 2183.98
   557.9 2183.42   567.6  2183.4   577.9  2183.4   667.2 2183.61     707 2185.08
   746.8 2188.83   766.7 2191.73   866.3 2200.58   905.8 2203.62   974.2 2210.56
   993.7 2213.31  1013.3 2216.87  1101.3 2248.67  1150.1  2255.4  1169.7 2257.17
#Mann= 3 , 0 , 0
       0      .1       0   557.9    .045       0   577.9      .1       0
Bank Sta=557.9,577.9
XS Rating Curve= 0 ,0
Exp/Cntr=0.3,0.1

Type RM Length L Ch R = 1 ,20298   ,375.3,364.2,352.5
XS GIS Cut Line= 3
     1955221.934      162171.175     1955565.838      161949.209
     1955916.677      161736.254
#Sta/Elev= 30
       0 2301.52    49.9  2281.1    59.9 2275.92    69.9  2269.5    89.8 2260.14
   109.8 2251.99   129.8 2244.59   149.8 2241.86   159.7 2238.53   179.7 2228.92
   239.6 2209.15   259.6 2201.64   289.5 2191.98   299.5  2188.9   319.5 2186.19
   349.4 2178.86   359.4 2177.44   399.3 2176.89   419.3 2176.89   448.4 2176.04
   477.7 2176.02   536.4 2176.41   585.2 2178.86   634.1 2182.51   653.6 2185.64
     722 2194.85   731.8 2196.86   741.6  2199.7   800.2 2208.55   819.7 2212.34
#Mann= 3 , 0 , 0
       0      .1       0   399.3    .045       0   419.3      .1       0
Bank Sta=399.3,419.3
XS Rating Curve= 0 ,0
Exp/Cntr=0.3,0.1

Type RM Length L Ch R = 1 ,19933.9 ,613.5,625.7,638
XS GIS Cut Line= 3
     1955556.106      162578.205     1955700.281      162383.302
     1956028.679      161835.972
#Sta/Elev= 30
       0 2344.16    19.4 2340.81    38.8 2334.91    67.9 2322.22    87.3  2311.3
   116.4 2298.77   126.1 2295.66   135.8 2294.32   203.6 2263.68   232.7 2247.22
   242.4 2245.06   252.4 2241.25   292.3 2220.24   352.1 2193.82   362.1 2192.72
   382.1 2183.33     412    2172     422 2170.48   434.3 2170.44   454.3 2170.48
   541.6 2167.04   601.5 2169.48   651.3 2182.06   671.3 2185.62   691.2 2186.65
     761 2199.47     791 2206.02   810.9 2208.62   830.9 2214.15   880.7 2231.14
#Mann= 3 , 0 , 0
       0      .1       0   434.3    .045       0   454.3      .1       0
Bank Sta=434.3,454.3
XS Rating Curve= 0 ,0
Exp/Cntr=0.3,0.1

Type RM Length L Ch R = 1 ,19307.5 ,210.1,209.5,207.8
XS GIS Cut Line= 2
     1955953.265      162688.968     1956685.475      162260.486
#Sta/Elev= 30
       0 2264.15    39.9 2252.43    59.9 2249.31    79.8 2242.51   149.7 2225.34
   169.7 2222.01   179.6 2218.04   209.6  2210.3   239.5  2204.5   259.5 2199.48
   279.5 2192.34   349.3 2173.26   369.3 2165.85   376.8 2164.04   396.8 2161.61
   419.2 2161.43   439.2 2162.62   449.1  2166.6   459.1 2174.76   548.9 2223.66
   558.9 2232.16   568.9 2238.66   608.8 2253.51   618.8 2256.29   658.7 2263.95
   708.6  2262.8   738.6 2260.06   768.5 2259.72   788.5 2261.11   848.4 2259.14
#Mann= 3 , 0 , 0
       0      .1       0   376.8    .045       0   396.8      .1       0
Bank Sta=376.8,396.8
XS Rating Curve= 0 ,0
Exp/Cntr=0.3,0.1

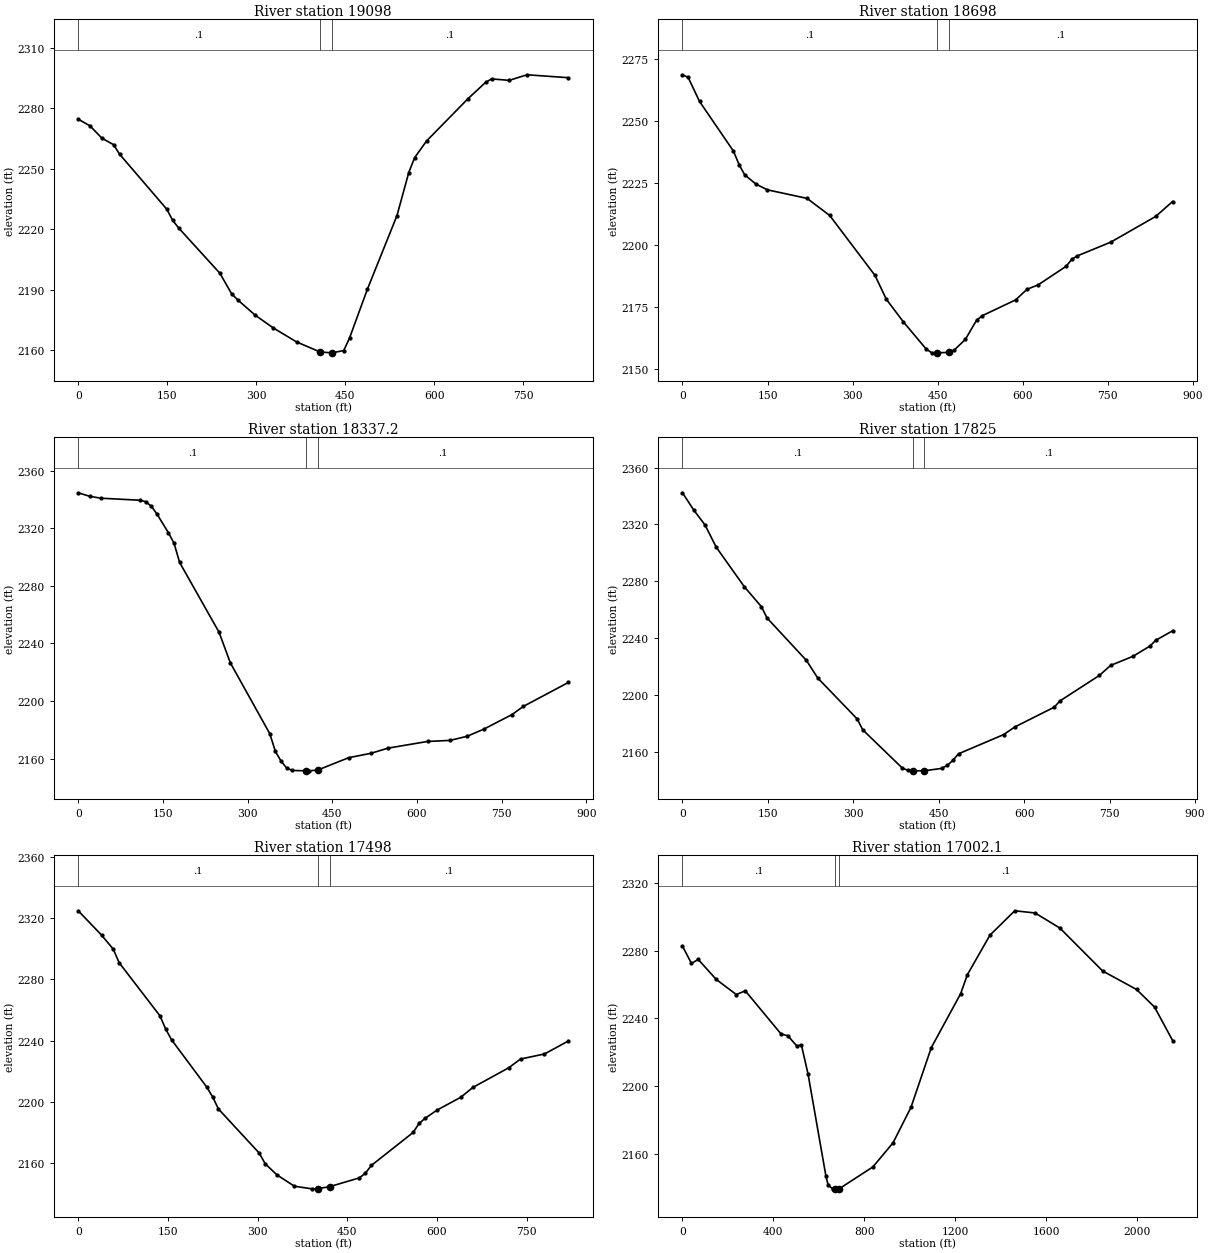
Type RM Length L Ch R = 1 ,19098   ,387.2,400.6,418
XS GIS Cut Line= 3
     1956051.589       162883.22     1956406.576      162663.538
     1956743.476      162433.234
#Sta/Elev= 30
       0  2274.5    19.9 2271.19    39.8  2265.1    59.6 2261.86    69.6 2257.17
   149.1 2229.92     159 2224.42     169 2220.62   238.6 2198.15   258.4 2187.92
   268.4    2185   298.2 2177.33     328 2171.13   367.8 2164.08   407.5  2159.1
   427.4 2158.68   427.5 2158.68   447.3 2159.82   457.3 2166.25   487.1 2190.24
   536.9  2226.7   556.8 2248.08   566.8 2255.49   586.7 2263.69   656.4 2284.63
   686.2 2292.77   696.2 2294.48     726 2293.77   755.9 2296.53   825.6 2295.08
#Mann= 3 , 0 , 0
       0      .1       0   407.5    .045       0   427.5      .1       0
Bank Sta=407.5,427.5
XS Rating Curve= 0 ,0
Exp/Cntr=0.3,0.1

Type RM Length L Ch R = 1 ,18698   ,367.1,359.7,349.4
XS GIS Cut Line= 3
     1956085.839      162990.201     1956543.886      163024.647
     1956944.339       163084.74
#Sta/Elev= 30
       0 2268.49      10 2267.44      30 2257.78    89.9 2237.77    99.9 2232.28
   109.8 2228.21   129.8 2224.47   149.8 2222.21   219.7 2218.76   259.6 2211.89
   339.5 2187.77   359.5 2178.18   389.4 2169.12   429.4 2158.25   439.4 2156.68
   449.3 2156.63   469.3 2156.82   479.1 2157.72   498.8 2162.03   518.6 2169.74
   528.5 2171.55   587.7 2177.96   607.5 2182.18   627.2 2183.97   676.6 2191.46
   686.5 2194.23   696.4 2195.64   755.6  2201.2   834.6 2211.52   864.3 2217.51
#Mann= 3 , 0 , 0
       0      .1       0   449.3    .045       0   469.3      .1       0
Bank Sta=449.3,469.3
XS Rating Curve= 0 ,0
Exp/Cntr=0.3,0.1

Type RM Length L Ch R = 1 ,18337.2 ,511,512.1,513.1
XS GIS Cut Line= 2
     1956190.121      163465.354     1957008.534      163176.263
#Sta/Elev= 30
       0 2344.58      20 2342.17    39.9 2340.83   109.7 2339.39   119.7 2338.39
   129.7 2335.13   139.7 2329.68   159.6 2316.92   169.6 2309.61   179.6 2296.21
   249.4 2247.78   269.4 2226.53   339.2 2177.41   349.2 2165.03   359.2 2158.35
   369.1 2153.57   379.1 2151.85   404.2 2151.62     409  2151.6   424.2 2152.17
   478.9 2160.71   518.8 2163.81   548.7 2167.36   618.6 2171.99   658.5 2172.72
   688.4 2175.56   718.3 2180.52   768.2 2190.65   788.2 2196.29     868 2212.93
#Mann= 3 , 0 , 0
       0      .1       0   404.2    .045       0   424.2      .1       0
Bank Sta=404.2,424.2
XS Rating Curve= 0 ,0
Exp/Cntr=0.3,0.1

Type RM Length L Ch R = 1 ,17825   ,324.7,327,327.9
XS GIS Cut Line= 2
     1956386.615      163916.033     1957208.776      163662.185
#Sta/Elev= 30
       0 2342.25    19.8 2330.11    39.6 2319.61    59.3 2303.99   108.8 2276.12
   138.5 2262.26   148.4 2254.32   217.6 2224.48   237.4 2212.16   306.6 2183.41
   316.5 2175.72   385.7 2148.96   395.6 2147.27   404.8 2146.94   405.5 2146.92
   424.8 2146.98     455 2148.63   464.8 2150.79   474.7 2154.21   484.6 2158.88
   563.8 2172.37   583.5 2177.74   652.8 2191.67   662.6    2196   731.9 2213.94
   751.7 2220.99   791.2  2227.4   820.9 2234.62   830.8 2238.59   860.5  2245.3
#Mann= 3 , 0 , 0
       0      .1       0   404.8    .045       0   424.8      .1       0
Bank Sta=404.8,424.8
XS Rating Curve= 0 ,0
Exp/Cntr=0.3,0.1

Type RM Length L Ch R = 1 ,17498   ,511.2,495.8,481.8
XS GIS Cut Line= 3
     1956462.606      164195.188     1956863.932      164110.083
     1957259.129      164003.308
#Sta/Elev= 30
       0 2324.82    39.1  2308.9    58.6 2299.76    68.4 2290.95   136.8 2256.18
   146.5  2247.4   156.3  2240.5   214.9 2209.77   224.7 2203.39   234.4 2195.49
   302.8 2166.63   312.6 2159.74   332.1 2152.52   361.4 2145.08   390.7 2143.35
   400.3 2143.45   420.3 2144.75   470.2 2150.52   480.1  2153.5   490.1 2158.59
     560 2180.13     570 2186.06     580 2189.34     600 2194.73   639.9 2203.16
   659.9 2209.51   719.8 2222.35   739.7 2228.06   779.7 2231.37   819.6 2239.84
#Mann= 3 , 0 , 0
       0      .1       0   400.3    .045       0   420.3      .1       0
Bank Sta=400.3,420.3
XS Rating Curve= 0 ,0
Exp/Cntr=0.3,0.1

Type RM Length L Ch R = 1 ,17002.1 ,305.4,330.8,356.3
XS GIS Cut Line= 4
     1956469.213      164449.807     1956911.612      164689.349
     1957233.233      164343.408     1958404.893      164198.836
#Sta/Elev= 30
       0 2282.75    39.5 2272.47      69 2274.89     148 2263.09   236.8  2254.1
   276.2 2256.31     434 2230.72   463.6 2229.75   503.1 2223.62   522.8 2224.41
   552.3 2207.11     631 2146.73   640.9  2141.4   660.5  2139.2   669.4  2139.2
   689.4 2139.24   837.7 2152.18   926.2 2166.42  1005.2 2187.42  1094.5 2222.72
  1223.4 2254.55  1253.2 2265.83  1352.4 2289.21  1461.6 2303.64  1550.8 2302.35
    1660 2293.44  1848.4 2268.02  1997.3 2257.11  2076.6  2246.7    2156 2226.92
#Mann= 3 , 0 , 0
       0      .1       0   669.4    .045       0   689.4      .1       0
Bank Sta=669.4,689.4
XS Rating Curve= 0 ,0
Exp/Cntr=0.3,0.1

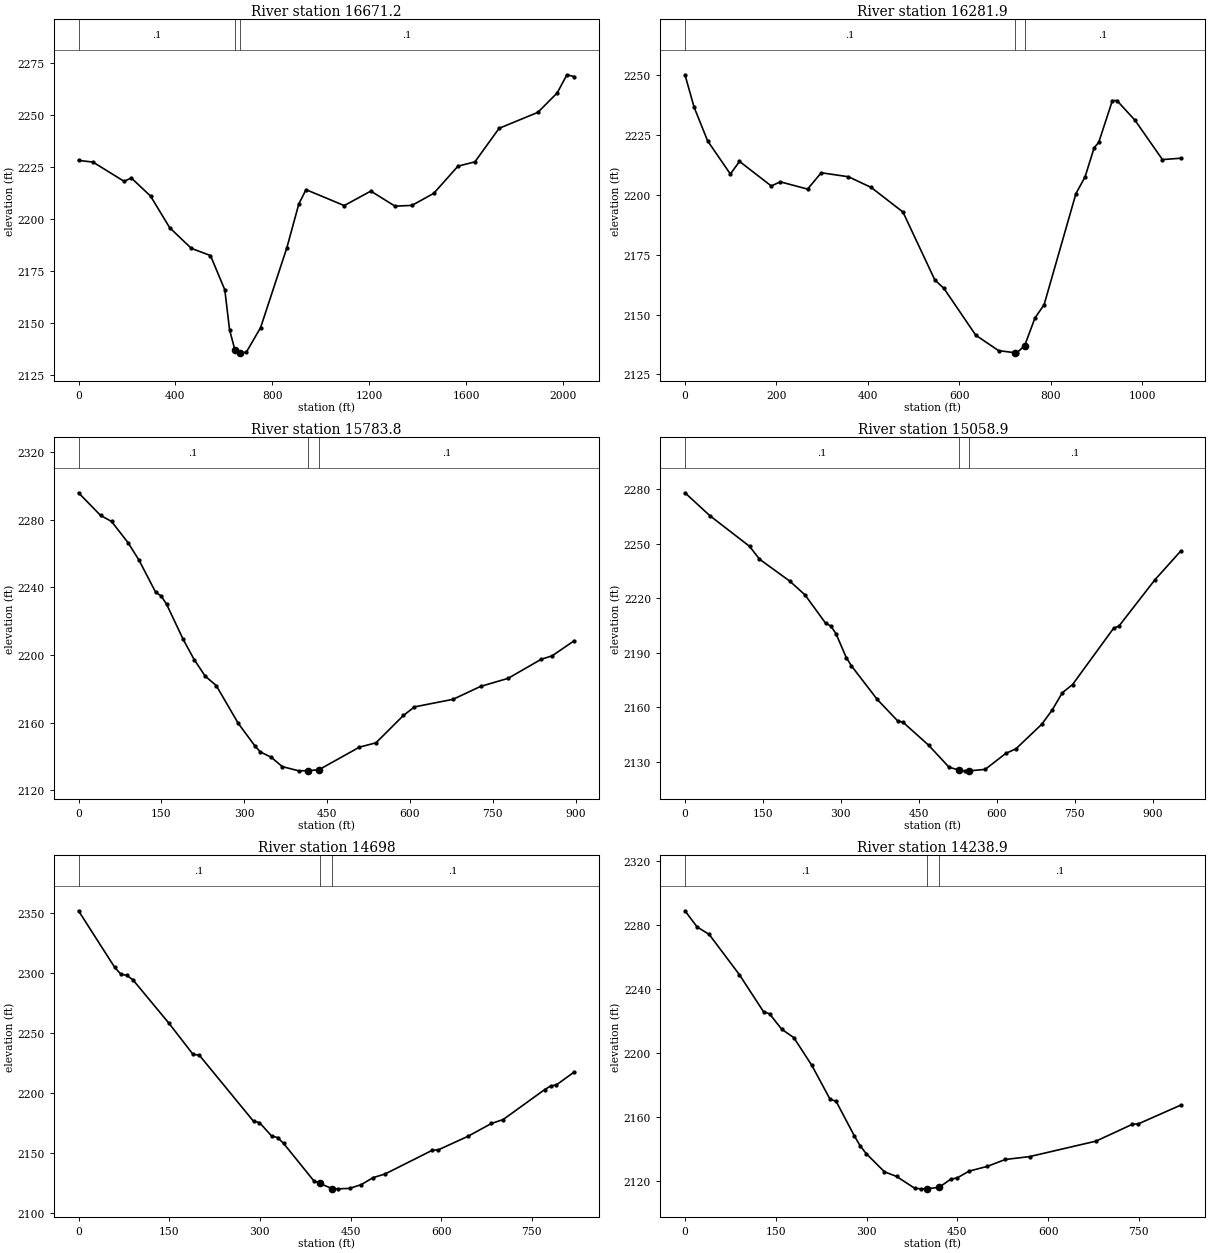
Type RM Length L Ch R = 1 ,16671.2 ,354.6,389.1,423.6
XS GIS Cut Line= 4
      1956557.32      164556.603     1956949.796      164807.574
     1957579.987      164924.541      1958482.32      164663.399
#Sta/Elev= 30
       0 2228.35    59.5 2227.55   188.3 2218.28   218.1  2219.9   297.4 2211.18
   376.6 2195.94   465.9 2186.03   544.7 2182.59   603.9 2166.11   623.6 2146.86
   646.1 2136.96   663.1 2135.78   666.1 2135.79   692.7 2136.07   751.8 2147.95
   860.3  2186.4   909.6 2207.45   939.2 2214.28    1097 2206.62  1206.7 2213.59
  1306.7 2206.34  1376.6 2206.71  1466.6 2212.51  1566.5 2225.58  1636.4 2227.65
  1736.4 2243.79  1896.3 2251.46  1976.2 2260.82  2016.2 2269.54  2046.2 2268.65
#Mann= 3 , 0 , 0
       0      .1       0   646.1    .045       0   666.1      .1       0
Bank Sta=646.1,666.1
XS Rating Curve= 0 ,0
Exp/Cntr=0.3,0.1

Type RM Length L Ch R = 1 ,16281.9 ,500.3,498.1,495.9
XS GIS Cut Line= 3
     1956437.174      164516.554      1956832.32      164764.855
     1956840.374      165381.946
#Sta/Elev= 30
       0 2250.19    19.9 2236.66    49.6 2222.53    99.3  2208.7   119.2 2213.99
   188.7 2203.72   208.5 2205.45   268.1 2202.41   297.9 2209.24   357.5 2207.57
   407.1 2203.11   476.6 2192.83   546.3 2164.46   566.2 2160.92   635.9 2141.34
   685.7  2134.9   722.7    2134   725.5 2133.98   742.7 2136.95   765.3 2148.56
   785.2 2154.06   854.9 2200.54   874.8 2207.51   894.7  2219.7   904.7 2221.93
   934.5 2239.38   944.5 2239.43   984.3 2231.11    1044 2214.75  1083.8 2215.31
#Mann= 3 , 0 , 0
       0      .1       0   722.7    .045       0   742.7      .1       0
Bank Sta=722.7,742.7
XS Rating Curve= 0 ,0
Exp/Cntr=0.3,0.1

Type RM Length L Ch R = 1 ,15783.8 ,732.7,724.3,715.9
XS GIS Cut Line= 2
     1956349.371      164427.335     1956407.805      165322.865
#Sta/Elev= 30
       0 2296.03    39.9 2282.64    59.8 2279.06    89.7 2266.51   109.7 2256.05
   139.6 2237.21   149.6 2235.01   159.5 2230.05   189.5  2209.3   209.4 2197.34
   229.3 2187.54   249.3 2181.99   289.2  2159.6   319.1 2146.38   329.1 2142.72
     349 2139.51     369 2133.99   398.9  2131.5   414.9 2131.61   434.9 2132.08
   508.6 2145.52   538.5 2148.07   588.3 2164.28   608.3 2169.34   678.1 2173.82
   727.9 2181.45   777.8 2186.23   837.6 2197.49   857.6 2199.56   897.4 2208.48
#Mann= 3 , 0 , 0
       0      .1       0   414.9    .045       0   434.9      .1       0
Bank Sta=414.9,434.9
XS Rating Curve= 0 ,0
Exp/Cntr=0.3,0.1

Type RM Length L Ch R = 1 ,15058.9 ,354.7,360.9,366.8
XS GIS Cut Line= 3
     1955710.961      164700.778     1955796.397      164860.972
     1956109.801      165566.411
#Sta/Elev= 30
       0 2278.13    47.8 2265.53   124.2 2248.66   143.3 2241.59   201.4 2229.53
     231 2221.88   270.6 2206.29   280.5 2204.77   290.4 2200.63   310.2 2187.44
   320.1 2182.88   369.6 2164.45   409.2 2152.52   419.1 2151.88   468.6 2139.18
   508.1    2127   526.5 2125.56   537.8 2125.04   546.5 2125.04   577.4 2125.82
     617  2134.6   636.8  2137.2   686.3 2150.68   706.1  2158.4   725.9 2168.02
   745.6 2172.55   824.8 2203.65   834.7 2204.68     904 2230.22   953.5 2245.98
#Mann= 3 , 0 , 0
       0      .1       0   526.5    .045       0   546.5      .1       0
Bank Sta=526.5,546.5
XS Rating Curve= 0 ,0
Exp/Cntr=0.3,0.1

Type RM Length L Ch R = 1 ,14698   ,463.5,459,454.8
XS GIS Cut Line= 3
      1955529.45      164872.961     1955599.922       165276.08
     1955673.414       165680.23
#Sta/Elev= 30
       0 2351.75    59.9 2304.64    69.9 2299.04    79.8 2297.94    89.8 2294.43
   149.7 2258.09   189.6 2232.15   199.6  2231.7   289.5 2176.56   299.4 2175.47
   319.4 2164.33   329.4 2162.98   339.4 2158.07   389.3 2126.95   399.2 2124.87
   419.2  2120.5   428.8 2120.31   448.4 2120.67   467.9 2123.84   487.5 2129.68
     507 2132.63   585.3 2152.42   595.1 2152.72     644 2163.97   683.1  2174.7
   702.6 2178.01   771.1 2202.87   780.9 2205.86   790.7 2206.86     820 2217.52
#Mann= 3 , 0 , 0
       0      .1       0   399.2    .045       0   419.2      .1       0
Bank Sta=399.2,419.2
XS Rating Curve= 0 ,0
Exp/Cntr=0.3,0.1

Type RM Length L Ch R = 1 ,14238.9 ,346,340.8,334.5
XS GIS Cut Line= 3
     1955023.792      165035.748     1955164.546      165420.298
     1955305.299      165804.848
#Sta/Elev= 30
       0 2288.84      20 2278.78      40 2274.09    89.9 2248.99   129.8 2225.87
   139.8 2224.55   159.8 2214.96   179.8 2209.73   209.7 2192.34   239.7  2171.3
   249.7 2170.01   279.7 2148.55   289.6 2142.15   299.6 2137.33   329.6 2126.03
   349.6 2123.14   379.5 2115.78   389.5  2115.4     400 2115.42     420 2116.38
   439.5 2121.51   449.4 2122.14   469.4 2126.45   499.4 2129.39   529.4 2133.72
   569.3  2135.5   679.2 2145.16   739.1 2155.63   749.1 2155.92     819 2167.59
#Mann= 3 , 0 , 0
       0      .1       0     400    .045       0     420      .1       0
Bank Sta=400,420
XS Rating Curve= 0 ,0
Exp/Cntr=0.3,0.1

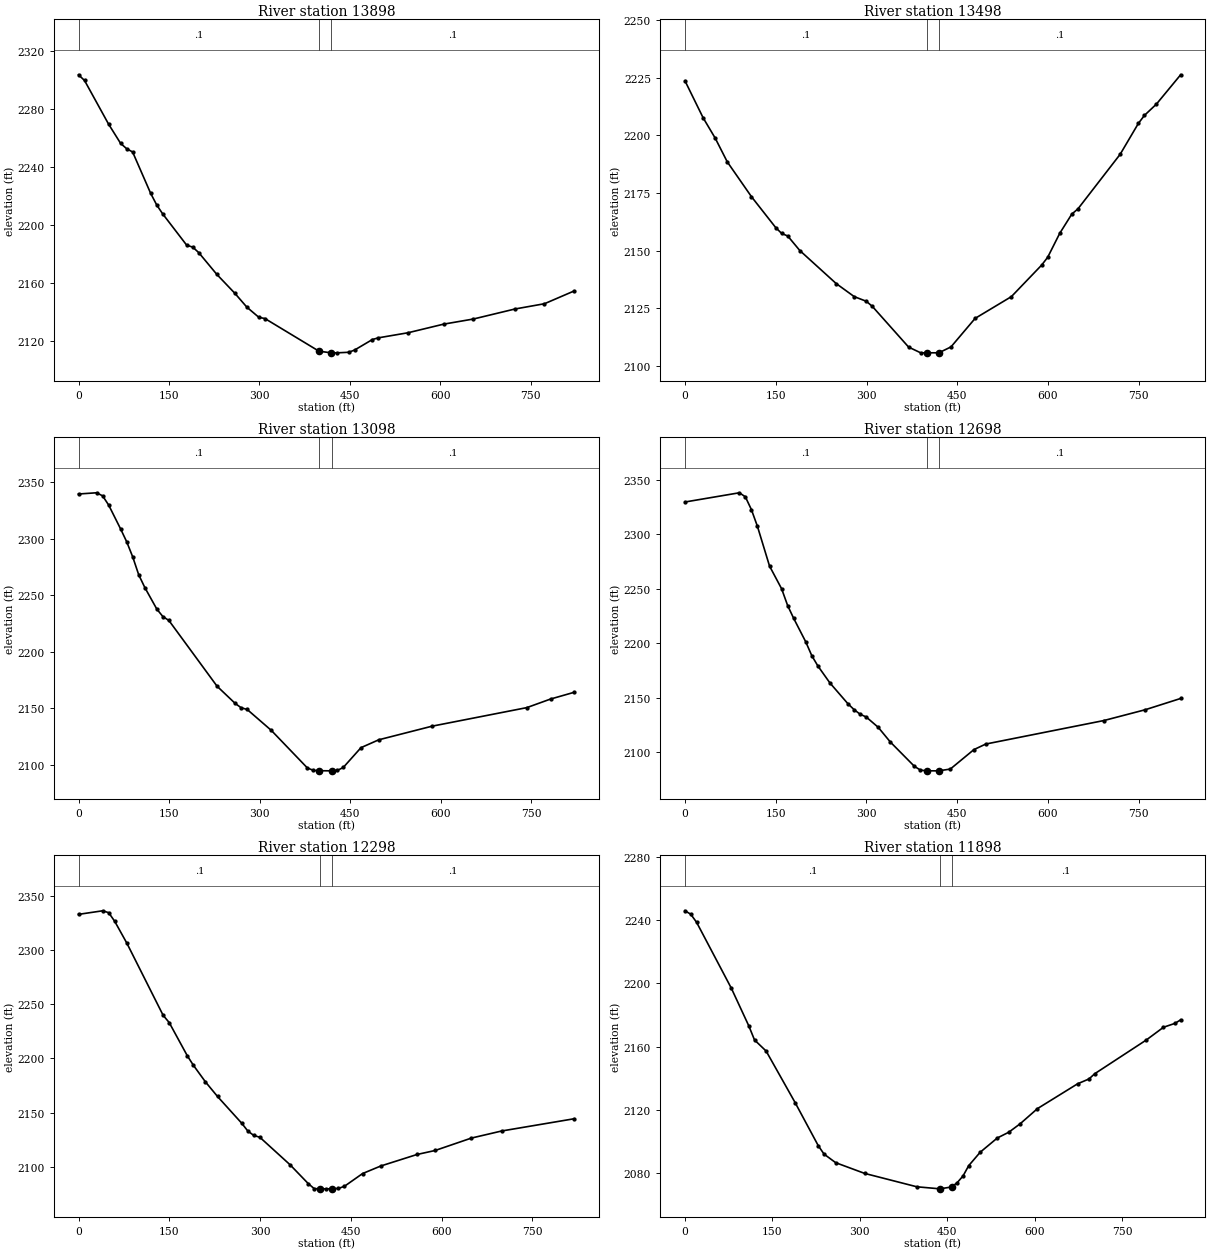
Type RM Length L Ch R = 1 ,13898   ,402.7,400,398.3
XS GIS Cut Line= 3
     1954631.921      165196.038     1954847.718      165543.068
     1955081.248      165883.706
#Sta/Elev= 30
       0 2303.61      10 2299.66    49.8 2269.57    69.8 2256.24    79.7 2252.61
    89.7  2250.3   119.6 2221.76   129.6 2213.75   139.5 2207.59   179.4 2185.92
   189.4 2184.61   199.3 2180.82   229.2 2165.83   259.2 2152.73   279.1 2143.16
     299 2136.13     309 2135.31   398.7 2112.74   418.7 2111.64   428.3 2111.62
     448 2112.01   457.8 2113.58   487.3 2120.83   497.2 2121.99   546.3 2125.49
   605.3 2131.43   654.5 2134.96   723.3 2141.87   772.5 2145.53   821.7 2154.35
#Mann= 3 , 0 , 0
       0      .1       0   398.7    .045       0   418.7      .1       0
Bank Sta=398.7,418.7
XS Rating Curve= 0 ,0
Exp/Cntr=0.3,0.1

Type RM Length L Ch R = 1 ,13498   ,400.9,400,401.6
XS GIS Cut Line= 3
     1954320.695      165505.846     1954573.001      165828.523
     1954825.548       166150.84
#Sta/Elev= 30
       0 2223.69      30 2207.64      50 2198.79    69.9 2188.51   109.9 2173.39
   149.9    2160   159.8 2157.44   169.8 2156.34   189.8 2150.02   249.8 2135.71
   279.7 2130.02   299.7    2128   309.7 2125.76   369.6 2108.11   389.6 2105.62
   399.6 2105.63   419.6 2105.64   439.6  2108.2   479.5 2120.58   539.4 2130.02
   589.4  2143.7   599.4  2147.1   619.3 2157.49   639.3 2165.86   649.3 2168.08
   719.2 2191.82   749.2 2205.18   759.2 2208.67   779.1 2213.59   819.1 2226.32
#Mann= 3 , 0 , 0
       0      .1       0   399.6    .045       0   419.6      .1       0
Bank Sta=399.6,419.6
XS Rating Curve= 0 ,0
Exp/Cntr=0.3,0.1

Type RM Length L Ch R = 1 ,13098   ,402.6,400,396.1
XS GIS Cut Line= 3
      1953964.19      165715.548     1954227.691      166028.439
     1954460.442      166368.363
#Sta/Elev= 30
       0 2339.47    29.9 2340.55    39.9 2337.84    49.9 2329.73    69.8 2308.48
    79.8 2297.22    89.8 2283.79    99.8 2267.88   109.8 2256.74   129.7 2237.63
   139.7 2231.04   149.7 2227.57   229.5 2169.39   259.4 2154.22   269.4 2150.34
   279.4 2148.81   319.3 2130.34   379.1 2097.07   389.1 2094.92   399.1 2094.62
   418.9 2094.52   419.1 2094.53   428.7 2094.89   438.5 2097.48   467.9 2115.03
   497.3 2121.98   585.6 2134.03   742.6 2150.46   781.8 2158.03     821 2164.02
#Mann= 3 , 0 , 0
       0      .1       0   399.1    .045       0   419.1      .1       0
Bank Sta=399.1,419.1
XS Rating Curve= 0 ,0
Exp/Cntr=0.3,0.1

Type RM Length L Ch R = 1 ,12698   ,400.4,400,398.3
XS GIS Cut Line= 3
     1953626.085      166001.393     1953921.192      166285.149
     1954202.645      166583.403
#Sta/Elev= 30
       0 2329.64    89.9 2338.11    99.8 2334.42   109.8  2322.7   119.8 2307.28
   139.8 2270.85   159.8 2249.97   169.8 2234.52   179.7 2222.87   199.7 2201.25
   209.7 2188.56   219.7 2179.17   239.6 2163.59   269.6 2144.35   279.6 2139.06
   289.6 2134.85   299.6 2132.33   319.5 2122.84   339.5 2109.36   379.4 2086.98
   389.4 2083.54   399.4  2082.9   419.2 2082.88   419.4 2082.88   438.7 2084.51
   477.7 2102.36   497.3 2107.47   692.6 2129.05   760.9 2138.95   819.5 2149.31
#Mann= 3 , 0 , 0
       0      .1       0   399.4    .045       0   419.4      .1       0
Bank Sta=399.4,419.4
XS Rating Curve= 0 ,0
Exp/Cntr=0.3,0.1

Type RM Length L Ch R = 1 ,12298   ,397.8,399.9,399.5
XS GIS Cut Line= 3
     1953334.445      166284.978     1953634.524      166563.622
     1953934.604      166842.266
#Sta/Elev= 30
       0 2333.06      40 2336.37    49.9  2334.6    59.9 2326.55    79.9 2306.42
   139.8 2239.83   149.8 2233.14   179.8 2202.38   189.8 2193.66   209.7 2178.34
   229.7  2164.8   269.7 2140.09   279.7 2132.94   289.6 2128.82   299.6 2127.14
   349.6 2101.71   379.5 2084.39   389.5 2079.64   399.5 2079.55   409.5 2079.49
   419.5 2079.49   429.5 2079.86   439.5 2081.88   469.4 2093.62   499.4 2100.58
   559.3 2111.22   589.3 2114.93   649.2 2126.39   699.2 2132.93     819 2144.24
#Mann= 3 , 0 , 0
       0      .1       0   399.5    .045       0   419.5      .1       0
Bank Sta=399.5,419.5
XS Rating Curve= 0 ,0
Exp/Cntr=0.3,0.1

Type RM Length L Ch R = 1 ,11898   ,414.2,414.3,416.7
XS GIS Cut Line= 3
     1953126.016      166569.072     1953427.875      166899.331
     1953727.554      167168.489
#Sta/Elev= 30
       0 2246.03     9.9 2243.84    19.9 2238.74    79.5 2196.96   109.4 2173.14
   119.3 2164.15   139.2 2157.12   188.9 2124.48   228.7 2097.11   238.6 2091.79
   258.5 2086.38   308.2 2079.58   397.7  2071.1   437.4  2069.8   457.4    2071
   467.1 2073.78   476.9 2077.93   486.7  2084.5   506.4    2093   535.8 2102.04
   555.5  2105.7   575.1 2111.08   604.6 2120.64   673.4 2136.36     693 2139.44
   702.9 2142.77   791.3 2164.13   820.8 2172.21   840.4 2174.66   850.2  2176.9
#Mann= 3 , 0 , 0
       0      .1       0   437.4    .045       0   457.4      .1       0
Bank Sta=437.4,457.4
XS Rating Curve= 0 ,0
Exp/Cntr=0.3,0.1

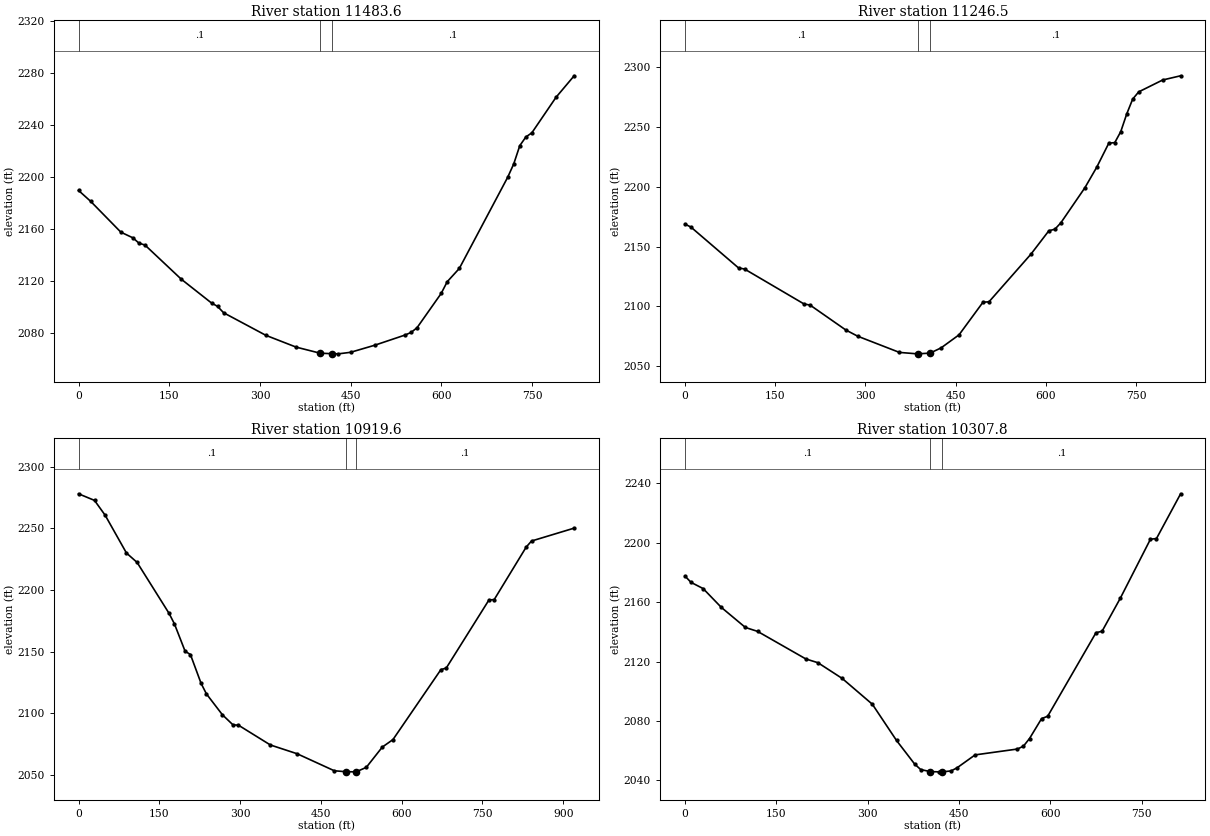
Type RM Length L Ch R = 1 ,11483.6 ,226.6,237,246.5
XS GIS Cut Line= 2
     1952796.766      166786.235      1953348.06      167392.588
#Sta/Elev= 30
       0 2189.52      20 2181.14      70 2157.35      90 2152.95    99.9  2148.9
   109.9 2147.41   169.9  2121.1   219.9 2102.75   229.9 2100.14   239.9 2095.23
   309.8 2077.83   359.8 2068.75   399.5 2064.06   419.5 2063.68   429.7 2063.57
   449.7 2064.74   489.7  2070.2   539.7 2078.03   549.7 2080.02   559.7 2083.69
   599.6  2110.1   609.6 2119.15   629.6 2129.38   709.6 2199.66   719.6 2209.95
   729.6 2224.03   739.6 2230.68   749.6 2233.95   789.5 2261.28   819.5 2277.87
#Mann= 3 , 0 , 0
       0      .1       0   399.5    .045       0   419.5      .1       0
Bank Sta=399.5,419.5
XS Rating Curve= 0 ,0
Exp/Cntr=0.3,0.1

Type RM Length L Ch R = 1 ,11246.5 ,322.5,326.8,332.1
XS GIS Cut Line= 3
     1952763.204      166864.035     1952896.523      167258.067
     1953073.432      167626.115
#Sta/Elev= 30
       0 2168.87     9.9 2166.37    89.1 2132.16      99 2131.27   198.1 2101.97
     208 2101.09   267.4 2080.24   287.2 2075.02   356.6 2061.45   386.3 2060.25
   387.6 2060.27   407.6 2060.85   425.9 2065.23   455.8 2076.17   495.6 2103.47
   505.6 2103.82   575.3 2143.68   605.2 2163.31   615.2  2164.6   625.1 2169.95
     665 2199.25   684.9 2216.61   704.8 2236.58   714.8 2237.13   724.7 2246.26
   734.7 2261.17   744.6 2273.57   754.6 2279.58   794.4 2289.52   824.3 2293.05
#Mann= 3 , 0 , 0
       0      .1       0   387.6    .045       0   407.6      .1       0
Bank Sta=387.6,407.6
XS Rating Curve= 0 ,0
Exp/Cntr=0.3,0.1

Type RM Length L Ch R = 1 ,10919.6 ,609.2,611.7,614.1
XS GIS Cut Line= 2
     1952515.086       166855.39     1952648.581      167765.827
#Sta/Elev= 30
       0 2278.07    29.7  2272.7    49.5 2260.66      89 2230.06   108.8 2222.42
   168.2 2181.08   178.1  2172.6   197.9 2150.46   207.8 2147.76   227.6 2124.37
   237.5 2115.87   267.2 2098.93   286.9 2090.74   296.8 2090.55   356.2 2074.48
   405.7  2067.4   474.9 2053.58     496 2052.83   514.5 2052.71     516 2052.82
   534.3 2056.34     564 2072.78   583.8 2078.86   672.8 2135.57   682.7 2136.81
   761.9 2191.94   771.8 2192.35   831.1 2234.84     841 2239.78   920.2 2250.23
#Mann= 3 , 0 , 0
       0      .1       0     496    .045       0     516      .1       0
Bank Sta=496,516
XS Rating Curve= 0 ,0
Exp/Cntr=0.3,0.1

Type RM Length L Ch R = 1 ,10307.8 ,394.1,409.8,419.8
XS GIS Cut Line= 2
     1951970.386       166936.58     1952010.475      167749.807
#Sta/Elev= 30
       0 2177.48     9.9 2173.24    29.8 2169.07    59.6 2156.45    99.3 2142.89
   119.2 2140.28   198.6 2121.72   218.4 2119.19   258.2 2108.64   307.8 2091.26
   347.5  2066.9   377.3 2051.02   387.2 2047.34   402.8 2045.96     417  2045.8
   422.8 2045.82   436.9 2046.39   446.8 2048.47   476.6  2057.2   546.1 2061.14
     556 2063.08     566 2068.22   585.8 2081.61   595.8 2083.18   675.2 2139.42
   685.1 2140.32   714.9 2162.41   764.6 2202.26   774.5  2202.7   814.2 2232.82
#Mann= 3 , 0 , 0
       0      .1       0   402.8    .045       0   422.8      .1       0
Bank Sta=402.8,422.8
XS Rating Curve= 0 ,0
Exp/Cntr=0.3,0.1