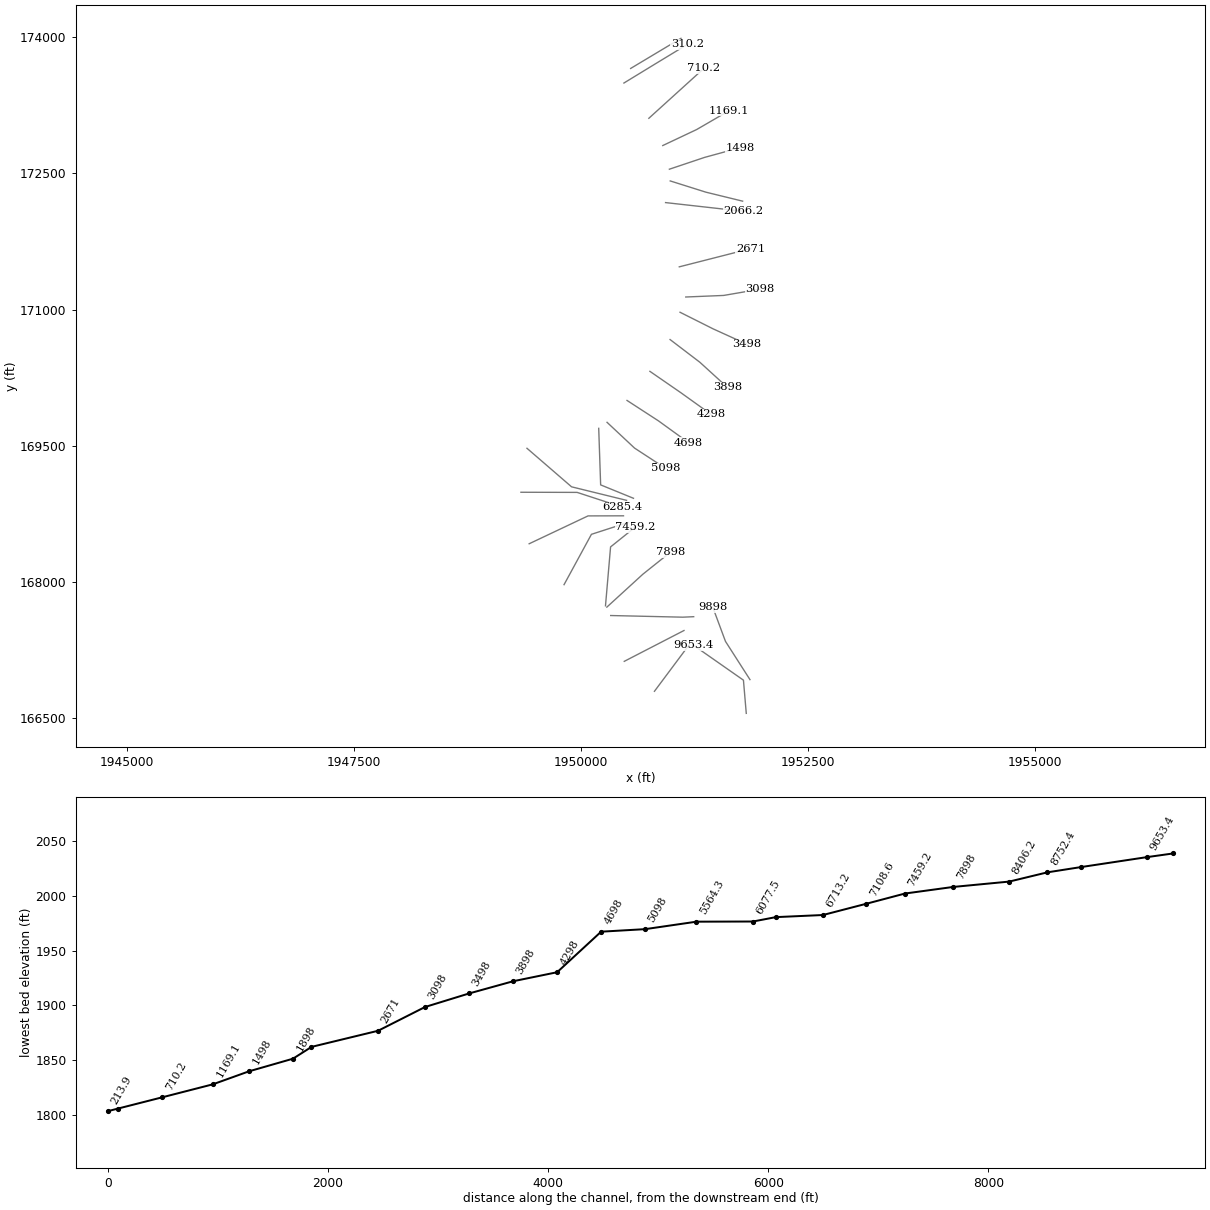
HEC-RAS study BrshCrk.prj: BrshCrk

--- BrshCrk.g01 (geometry) --- (continued)

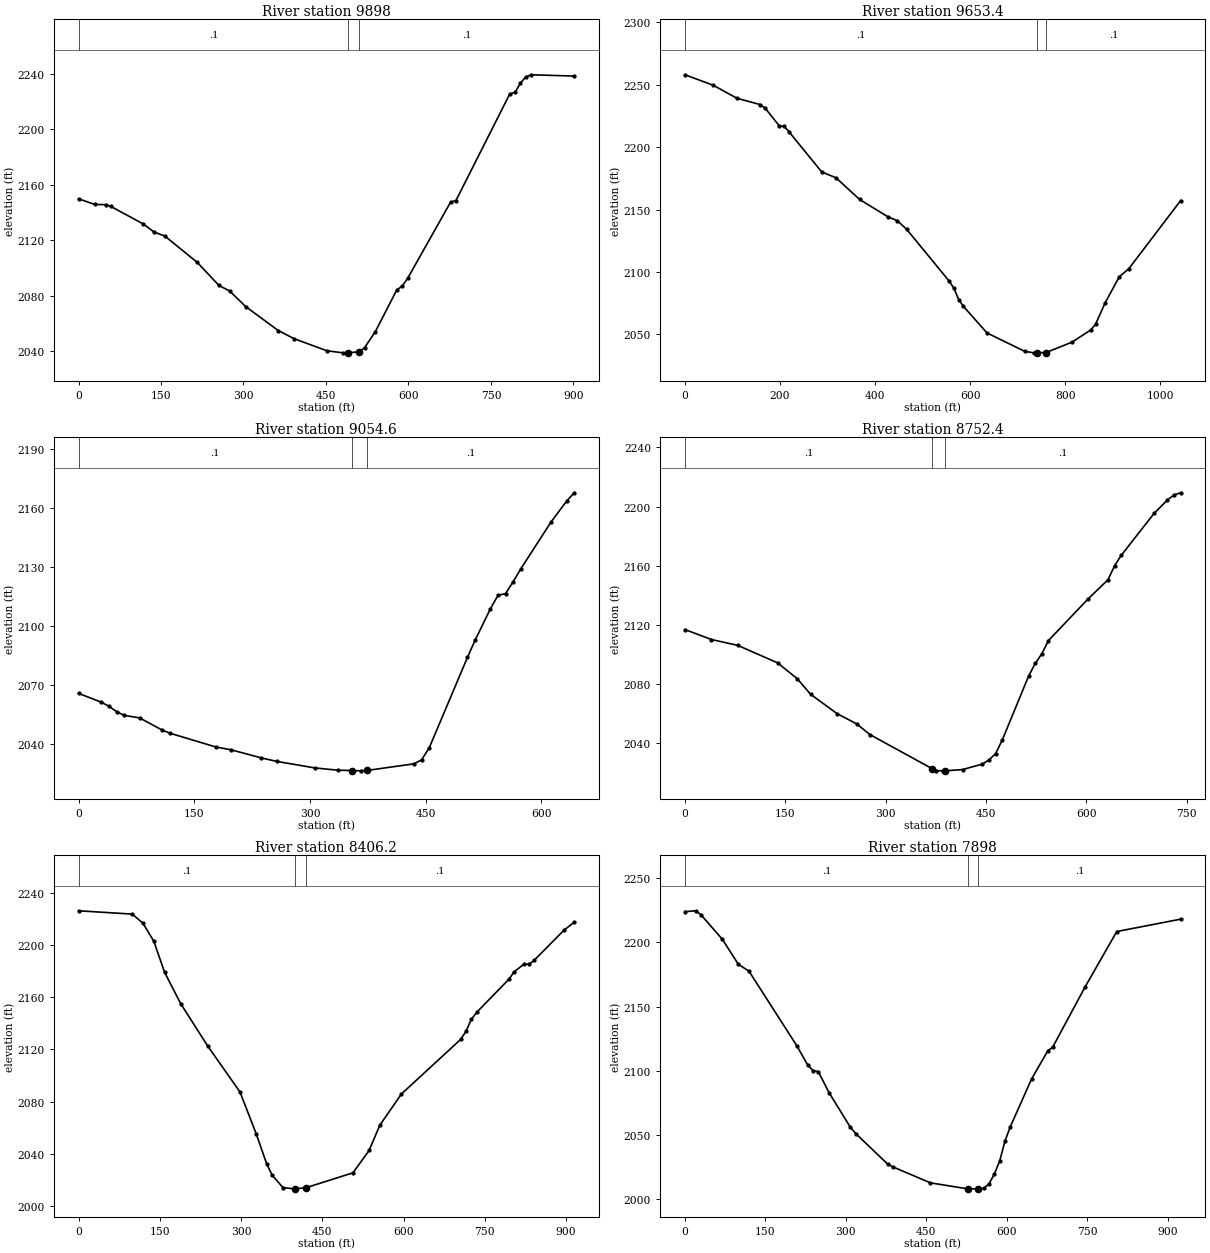
Type RM Length L Ch R = 1 ,9898    ,235.1,244.5,259.5
XS GIS Cut Line= 3
     1951861.697      166922.976     1951591.662      167344.571
     1951452.199      167720.187
#Sta/Elev= 30
       0 2149.74    29.4  2145.7    49.1  2145.5    58.9  2144.2   117.8  2131.6
   137.4 2125.78   157.1 2122.86     216 2103.87   255.2 2087.36   274.9 2083.22
   304.3 2071.99   363.2 2054.79   392.7 2048.81   451.6 2040.22     481 2038.72
   490.7 2038.72   510.7 2039.55   520.2 2042.46   539.8 2054.03   578.8  2084.1
   588.6 2086.82   598.4 2092.34   676.6 2147.38   686.3 2148.45   784.1 2225.24
   793.8 2226.48   803.6 2233.11   813.4 2237.64   823.2 2239.12   901.3 2238.19
#Mann= 3 , 0 , 0
       0      .1       0   490.7    .045       0   510.7      .1       0
Bank Sta=490.7,510.7
XS Rating Curve= 0 ,0
Exp/Cntr=0.3,0.1

Type RM Length L Ch R = 1 ,9653.4  ,639.1,599,558.8
XS GIS Cut Line= 3
     1951820.911      166551.021     1951789.778      166916.943
     1951236.203      167303.933
#Sta/Elev= 30
       0 2257.94    59.6 2249.54   109.2 2239.15   158.8 2234.02   168.7 2231.16
   198.5    2217   208.4 2216.75   218.4 2212.49   287.8 2180.08   317.6 2175.48
   367.2 2158.14   426.8 2144.24   446.7 2141.13   466.6 2134.07     556 2092.63
   565.9 2086.87   575.8  2077.9   585.8 2072.45   635.4 2051.19   714.9 2036.43
   734.8 2035.27   739.6  2035.3   759.6 2035.54   814.2 2043.81     854  2053.7
   863.9 2058.27   883.8 2075.26   913.6 2096.17   933.4  2102.5  1042.7  2157.2
#Mann= 3 , 0 , 0
       0      .1       0   739.6    .045       0   759.6      .1       0
Bank Sta=739.6,759.6
XS Rating Curve= 0 ,0
Exp/Cntr=0.3,0.1

Type RM Length L Ch R = 1 ,9054.6  ,313.5,301.7,289.9
XS GIS Cut Line= 2
     1950809.123      166794.371     1951193.484      167309.273
#Sta/Elev= 30
       0 2065.65    29.7 2061.14    39.5 2059.05    49.4 2056.32    59.3 2054.42
    79.1 2053.17   108.7 2046.89   118.6 2045.34   177.9 2038.35   197.7 2036.91
   237.2 2032.74     257 2030.99   306.4 2027.66   336.1 2026.51   354.1 2026.34
   365.8 2026.18   374.1 2026.39     435 2029.76   444.8  2031.8   454.7 2037.97
   504.2 2084.01     514 2092.65   533.8 2108.65   543.7 2115.55   553.6  2116.5
   563.5 2122.58   573.3 2129.09   612.9 2153.19   632.6 2163.53   642.5 2167.85
#Mann= 3 , 0 , 0
       0      .1       0   354.1    .045       0   374.1      .1       0
Bank Sta=354.1,374.1
XS Rating Curve= 0 ,0
Exp/Cntr=0.3,0.1

Type RM Length L Ch R = 1 ,8752.4  ,358.6,346.6,334.5
XS GIS Cut Line= 2
      1950476.56      167124.366     1951134.746      167464.128
#Sta/Elev= 30
       0 2116.93    39.5  2110.2      79 2106.21   138.3 2094.44   167.9 2083.66
   187.6 2073.22   227.2 2060.12   256.8 2053.11   276.5  2045.9   369.1 2022.95
   375.3 2021.53   385.2 2021.42   389.1 2021.45   414.8 2022.28   444.4 2025.98
   454.3  2028.8   464.2 2033.08     474 2042.08   513.6 2085.58   523.4 2094.01
   533.3 2100.57   543.2  2109.5   602.4 2137.65   632.1 2150.57     642 2160.06
   651.8 2167.02   701.2 2195.57     721 2204.53   730.8 2207.92   740.7 2209.39
#Mann= 3 , 0 , 0
       0      .1       0   369.1    .045       0   389.1      .1       0
Bank Sta=369.1,389.1
XS Rating Curve= 0 ,0
Exp/Cntr=0.3,0.1

Type RM Length L Ch R = 1 ,8406.2  ,488.7,507.8,525.3
XS GIS Cut Line= 3
     1950326.995      167629.238     1951121.397      167610.972
     1951241.542      167616.312
#Sta/Elev= 30
       0 2226.52    99.3 2223.96   119.2 2216.83   139.1 2203.05   158.9 2179.24
   188.7 2155.15   238.4 2122.71     298 2087.41   327.8 2055.46   347.6 2031.85
   357.6 2023.36   377.4 2013.97   397.3 2012.98   400.3 2013.02   420.3  2013.9
   506.6 2025.28   536.4 2042.47   556.2 2061.87     596 2085.81   705.2 2127.67
   715.2 2133.93   725.1 2143.14     735 2148.52   794.6 2174.05   803.9 2179.61
   822.4 2185.59   831.6 2185.46   840.9 2188.42   896.4 2211.74   914.9  2217.7
#Mann= 3 , 0 , 0
       0      .1       0   400.3    .045       0   420.3      .1       0
Bank Sta=400.3,420.3
XS Rating Curve= 0 ,0
Exp/Cntr=0.3,0.1

Type RM Length L Ch R = 1 ,7898    ,420,438.7,459
XS GIS Cut Line= 3
     1950284.721      167721.783     1950681.205      168084.079
     1950983.564      168325.608
#Sta/Elev= 30
       0 2223.88    19.9 2224.57    29.8 2221.47    69.6 2202.41    99.5 2182.92
   119.4 2177.52   208.9 2119.21   228.8 2104.52   238.7 2100.22   248.6 2099.35
   268.5 2083.07   308.3 2056.08   318.3 2051.16     378 2027.31   387.9 2025.16
   457.5 2012.76   527.1  2008.1   547.1  2008.1   556.9 2008.47   566.8 2012.01
   576.8 2019.58   586.7 2029.76   596.6 2045.35   606.5 2056.39   646.2 2093.66
     676 2115.23   685.9 2118.65   745.5 2164.95     805 2208.42   924.1 2218.04
#Mann= 3 , 0 , 0
       0      .1       0   527.1    .045       0   547.1      .1       0
Bank Sta=527.1,547.1
XS Rating Curve= 0 ,0
Exp/Cntr=0.3,0.1

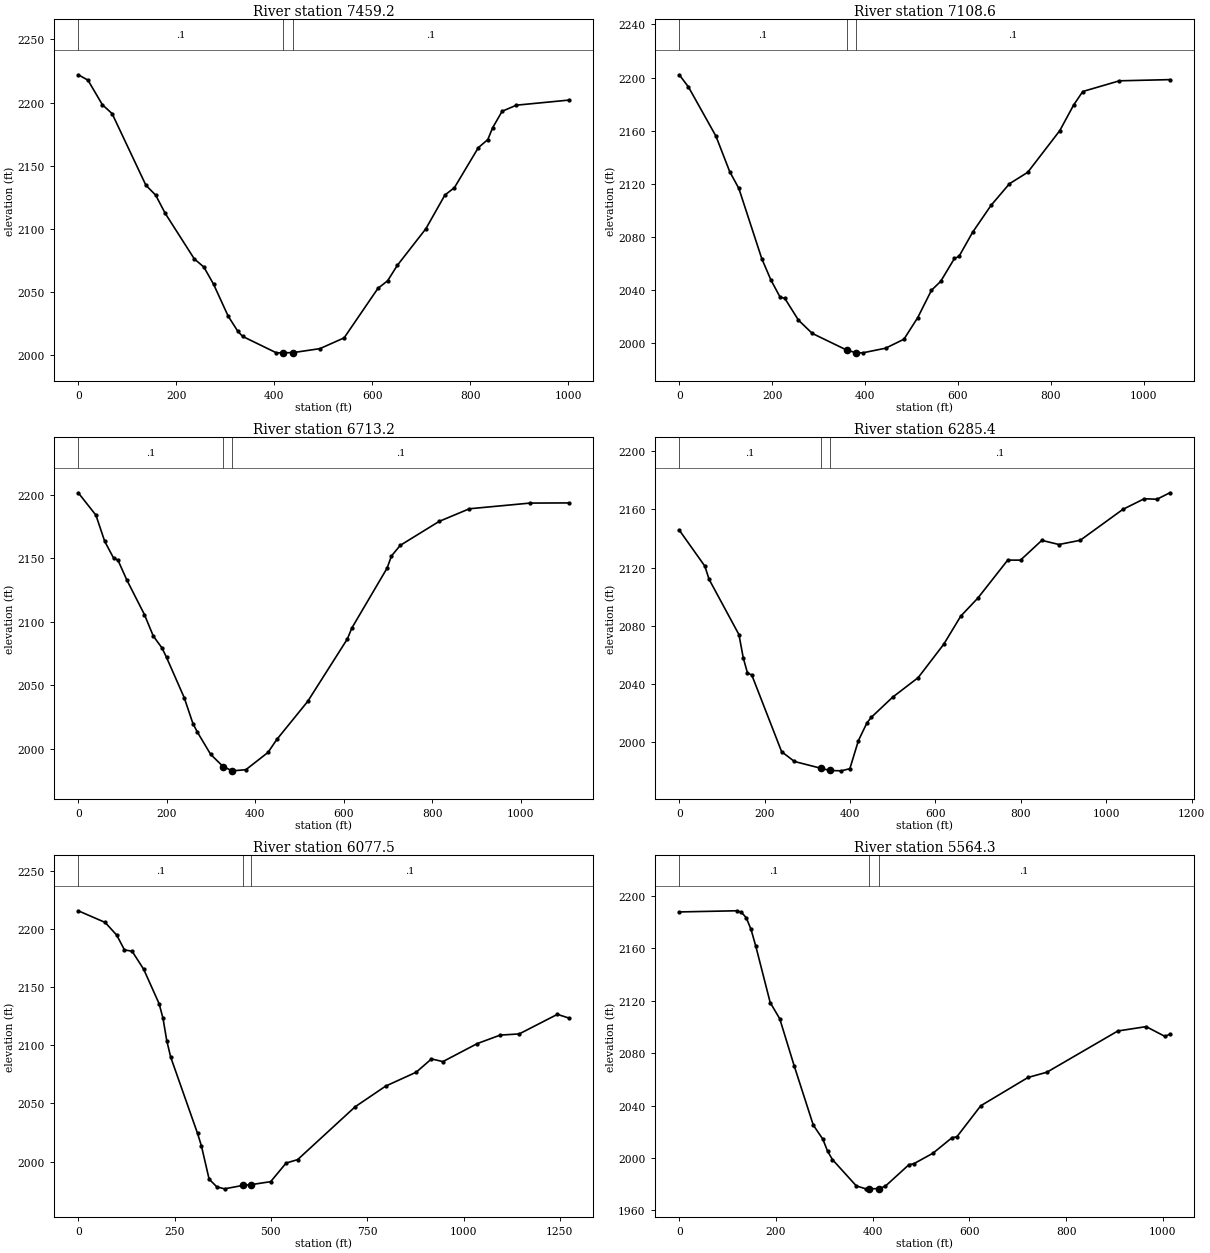
Type RM Length L Ch R = 1 ,7459.2  ,360.9,350.5,340.2
XS GIS Cut Line= 3
     1950269.698      167736.458     1950325.766      168385.244
     1950598.976      168604.315
#Sta/Elev= 30
       0 2222.02    19.7 2217.81    49.3  2198.3    69.1  2191.3   138.1 2134.62
   157.9 2126.89   177.6 2112.35   236.8 2076.43   256.5  2069.9   276.3 2056.28
   305.9  2031.2   325.6 2019.19   335.5 2015.08   404.5 2002.08   417.7 2002.14
   437.7 2002.21   493.3  2005.4   542.7 2013.92   611.7 2053.07   631.5 2059.07
   651.2 2071.22   709.6 2100.26   748.5 2126.91   767.9 2132.75   816.6 2164.33
     836 2170.76   845.8 2180.06   865.2 2193.14   894.4 2197.98  1001.4 2201.99
#Mann= 3 , 0 , 0
       0      .1       0   417.7    .045       0   437.7      .1       0
Bank Sta=417.7,437.7
XS Rating Curve= 0 ,0
Exp/Cntr=0.3,0.1

Type RM Length L Ch R = 1 ,7108.6  ,411.2,395.3,379.4
XS GIS Cut Line= 3
     1949813.056      167969.182     1950114.843      168524.079
     1950518.359      168654.586
#Sta/Elev= 30
       0 2202.11    19.7    2193      79 2155.87   108.6 2129.18   128.3 2116.51
   177.6 2063.66   197.4 2047.51   217.1 2034.67     227 2033.86   256.6 2017.37
   286.2  2007.4     360 1994.91     380 1992.86   394.8 1992.76   444.1 1996.25
   483.6 2003.02   513.2 2019.26   542.8 2039.86   562.6 2046.54   592.2 2063.79
     602 2065.32   631.6 2083.66   671.1 2103.82   710.6 2120.06     750 2128.68
     819 2160.07   848.6 2179.21   868.4 2189.51   947.3 2197.57  1055.8 2198.46
#Mann= 3 , 0 , 0
       0      .1       0     360    .045       0     380      .1       0
Bank Sta=360,380
XS Rating Curve= 0 ,0
Exp/Cntr=0.3,0.1

Type RM Length L Ch R = 1 ,6713.2  ,438.9,427.7,416.5
XS GIS Cut Line= 3
     1949428.678      168419.953     1950077.465      168726.992
     1950468.201      168727.899
#Sta/Elev= 30
       0 2201.68    39.9 2184.04    59.8 2163.37    79.8  2150.2    89.7 2148.57
   109.7 2132.94   149.5 2105.67   169.5 2088.74   189.4 2079.24   199.4 2071.92
   239.3 2040.25   259.2 2019.64   269.2 2012.97   299.1 1995.45   327.3 1985.81
   347.3 1982.54   348.9 1982.44   378.8 1983.35   428.7 1996.94   448.6 2007.15
   518.4 2037.16   608.1 2086.42   618.1 2094.99   697.8 2142.24   707.8 2151.87
   727.5  2160.2   815.5 2179.12   883.8 2189.07  1020.6 2193.55  1108.5 2193.69
#Mann= 3 , 0 , 0
       0      .1       0   327.3    .045       0   347.3      .1       0
Bank Sta=327.3,347.3
XS Rating Curve= 0 ,0
Exp/Cntr=0.3,0.1

Type RM Length L Ch R = 1 ,6285.4  ,225.7,207.9,190
XS GIS Cut Line= 3
     1949338.036      168987.488     1949957.319      168985.973
     1950460.447      168821.362
#Sta/Elev= 30
       0 2145.66    59.9 2120.95    69.9 2111.86   139.8 2073.96   149.8 2058.12
   159.8 2047.55   169.8 2046.32   239.7 1993.66   269.7 1986.94   332.3 1982.24
   352.3 1980.79   379.6 1980.52   399.5 1982.02   419.5 2001.25   439.5 2013.42
   449.5 2017.17   499.4 2030.98   559.4 2044.44   619.3 2067.34   659.2 2086.65
   699.2 2099.02   769.1 2125.07   799.1 2125.06     849 2138.62     889 2135.78
   938.9 2138.67  1038.8 2159.88  1088.7 2167.15  1118.7 2166.84  1148.7 2171.26
#Mann= 3 , 0 , 0
       0      .1       0   332.3    .045       0   352.3      .1       0
Bank Sta=332.3,352.3
XS Rating Curve= 0 ,0
Exp/Cntr=0.3,0.1

Type RM Length L Ch R = 1 ,6077.5  ,533.7,513,492.3
XS GIS Cut Line= 3
     1949404.649      169471.895     1949895.911       169047.38
     1950501.831      168898.465
#Sta/Elev= 30
       0 2215.79    69.9 2205.74    99.9 2194.79   119.9 2182.14   139.8 2180.96
   169.8 2165.47   209.8 2135.86   219.8 2123.46   229.7 2104.06   239.7 2090.07
   309.6 2024.19   319.6 2013.53   339.6 1984.87   359.6 1978.24   379.6 1976.51
   428.4 1979.54   448.4 1980.11   499.4 1982.69   539.4 1998.68   569.4 2001.66
   718.6 2047.12   797.8 2064.91   877.1 2076.88   916.7 2088.31   946.4    2086
  1035.5  2101.5    1095  2108.8  1144.5 2109.82  1243.5 2126.67  1273.2  2123.5
#Mann= 3 , 0 , 0
       0      .1       0   428.4    .045       0   448.4      .1       0
Bank Sta=428.4,448.4
XS Rating Curve= 0 ,0
Exp/Cntr=0.3,0.1

Type RM Length L Ch R = 1 ,5564.3  ,446.3,466.2,490.4
XS GIS Cut Line= 3
     1950195.044      169691.828       1950216.3       169068.74
     1950578.159      168921.024
#Sta/Elev= 30
       0 2187.92   118.8  2188.8   128.6 2187.65   138.5 2183.48   148.4 2174.57
   158.3  2161.7     188 2118.72   207.8 2106.28   237.5  2070.5   277.1 2025.08
   296.9 2014.29   306.8 2005.03   316.7 1998.73   366.2 1978.57     386 1976.36
     392 1976.37     412 1976.53   425.5 1978.18     475 1994.86   484.9 1995.53
   524.5 2003.56   564.1 2015.47     574 2016.12   623.4 2039.84   721.2 2061.46
   760.2 2065.47   906.8 2096.96   965.4 2100.29  1004.5 2092.77  1014.3 2094.57
#Mann= 3 , 0 , 0
       0      .1       0     392    .045       0     412      .1       0
Bank Sta=392,412
XS Rating Curve= 0 ,0
Exp/Cntr=0.3,0.1

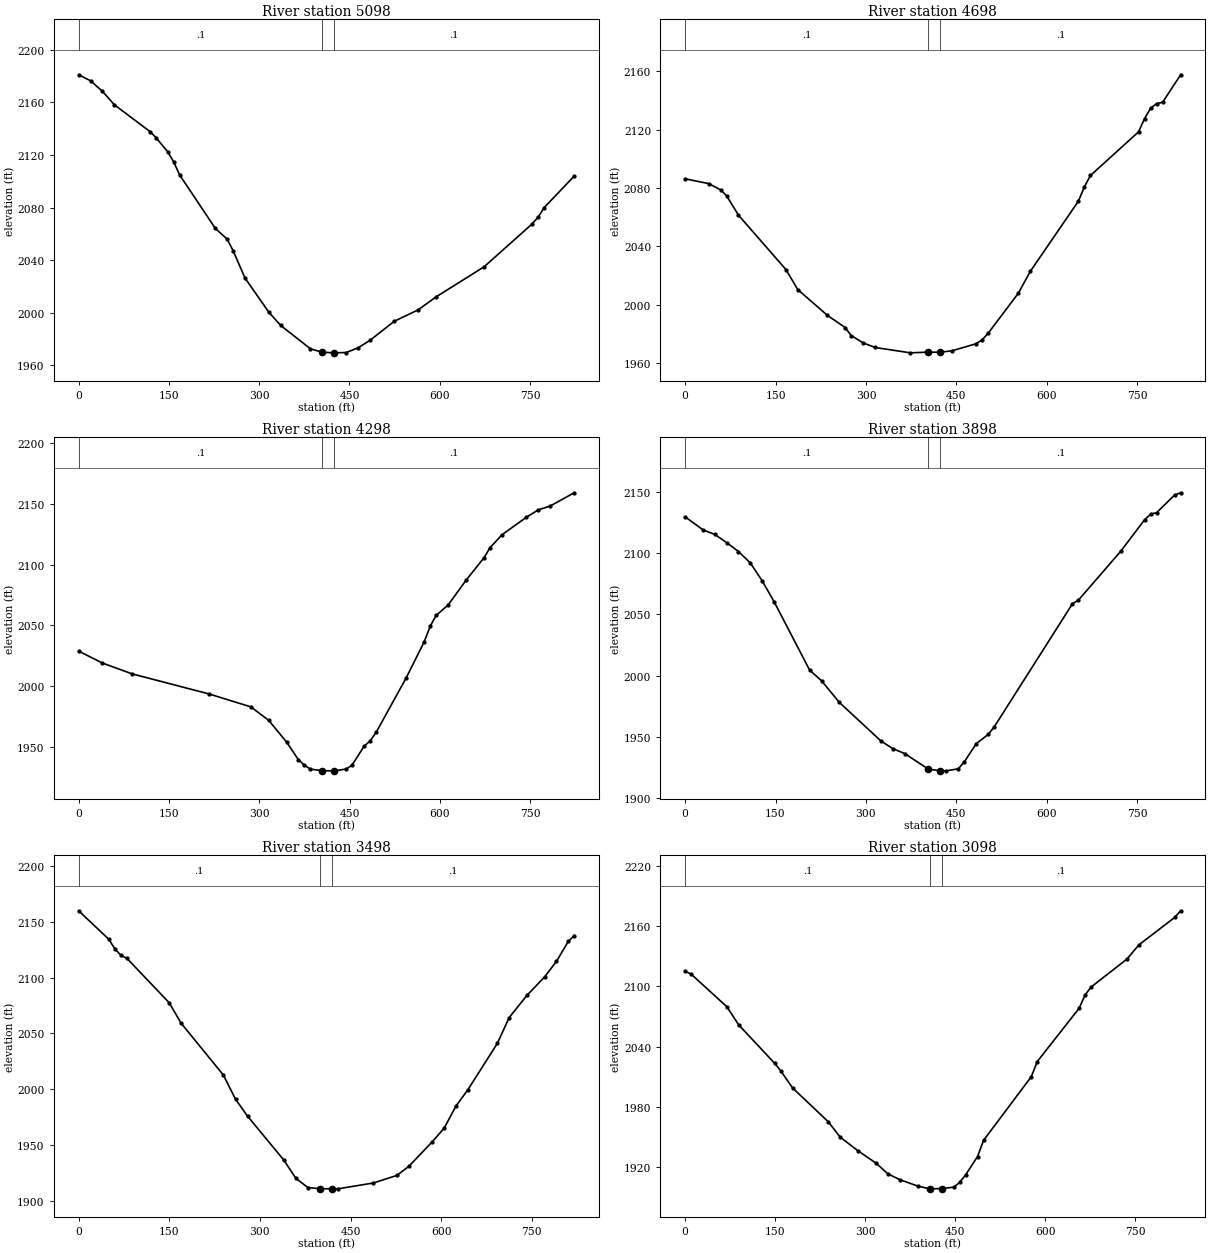
Type RM Length L Ch R = 1 ,5098    ,395.6,400,398.8
XS GIS Cut Line= 3
     1950286.975      169757.916     1950589.616      169474.434
     1950931.723      169251.038
#Sta/Elev= 30
       0 2181.03    19.8 2176.47    39.5 2168.49    59.2 2158.27   118.5 2137.86
   128.4 2133.32   148.1 2122.41     158 2114.72   167.8 2104.85   227.1 2064.18
   246.8 2056.02   256.7 2047.19   276.4 2026.45   315.9 2000.49   335.7 1990.38
     385 1972.67   404.7 1969.99   424.6 1969.54   424.7 1969.54   444.6 1969.78
   464.5  1973.4   484.4 1979.15   524.3 1993.52   564.2 2002.25     594 2012.14
   673.8 2035.03   753.5 2067.61   763.5 2072.81   773.4 2079.96   823.3 2103.94
#Mann= 3 , 0 , 0
       0      .1       0   404.7    .045       0   424.7      .1       0
Bank Sta=404.7,424.7
XS Rating Curve= 0 ,0
Exp/Cntr=0.3,0.1

Type RM Length L Ch R = 1 ,4698    ,400.5,399.8,400
XS GIS Cut Line= 3
     1950506.969      169999.059     1950853.354      169774.111
     1951184.642      169534.465
#Sta/Elev= 30
       0 2086.32    39.3    2083      59 2078.71    68.8  2074.7    88.5 2061.44
   167.2 2024.24   186.8 2010.55     236 1992.86   265.5 1984.54   275.4 1979.06
     295 1974.13   314.7 1970.91   373.7 1967.22     403  1967.7     423 1967.62
   442.9 1968.65   482.8 1973.46   492.8 1976.15   502.8 1980.71   552.6 2007.95
   572.6 2022.98   652.4 2071.05   662.3 2080.82   672.3 2088.57   752.1 2118.43
   762.1 2127.56     772 2134.59     782 2137.73     792 2138.67   821.9 2157.48
#Mann= 3 , 0 , 0
       0      .1       0     403    .045       0     423      .1       0
Bank Sta=403,423
XS Rating Curve= 0 ,0
Exp/Cntr=0.3,0.1

Type RM Length L Ch R = 1 ,4298    ,401,399.9,396.9
XS GIS Cut Line= 3
     1950759.044      170319.793     1951099.964      170084.494
     1951432.117      169846.477
#Sta/Elev= 30
       0 2028.74    39.4 2018.96    88.8 2010.02     217 1993.42     286 1982.84
   315.6 1971.77   345.2 1953.97   364.9 1939.38   374.8 1934.89   384.6 1931.66
   404.2 1930.26   424.2 1930.18   444.1 1931.64   454.1 1934.89     474 1950.42
     484 1954.82     494 1961.81   543.8 2006.58   573.7 2036.26   583.7 2049.06
   593.6 2058.09   613.6 2066.73   643.5 2087.18   673.4 2105.77   683.3    2114
   703.3 2124.64   743.1  2138.8   763.1 2144.98     783 2148.19   822.9 2159.11
#Mann= 3 , 0 , 0
       0      .1       0   404.2    .045       0   424.2      .1       0
Bank Sta=404.2,424.2
XS Rating Curve= 0 ,0
Exp/Cntr=0.3,0.1

Type RM Length L Ch R = 1 ,3898    ,395.4,400,407.8
XS GIS Cut Line= 3
     1950981.278      170670.193     1951310.023      170419.546
     1951612.125      170144.116
#Sta/Elev= 30
       0 2129.97    29.5 2119.31    49.2 2115.51    68.9 2108.82    88.6 2101.52
   108.3 2092.11     128 2077.44   147.6 2060.48   206.7 2004.36   226.4 1995.72
   255.9 1977.98   324.8 1946.45   344.5 1940.13   364.2 1936.12   403.4  1923.4
   423.4 1921.98   433.3 1921.94   453.3 1923.62   463.2 1929.21   483.2 1944.28
   503.1 1951.82   513.1 1958.08   642.7 2058.73   652.7 2061.77   722.5 2101.54
   762.4 2127.53   772.4 2132.13   782.3 2133.28   812.2  2147.8   822.2 2149.61
#Mann= 3 , 0 , 0
       0      .1       0   403.4    .045       0   423.4      .1       0
Bank Sta=403.4,423.4
XS Rating Curve= 0 ,0
Exp/Cntr=0.3,0.1

Type RM Length L Ch R = 1 ,3498    ,387.2,399.9,414.8
XS GIS Cut Line= 3
     1951091.129      170970.813     1951456.968      170787.292
     1951830.812      170617.272
#Sta/Elev= 30
       0 2159.97    49.9 2134.48    59.9 2125.85    69.9 2120.13    79.9  2117.3
   149.7 2077.64   169.7 2059.16   239.6  2012.7   259.6  1991.1   279.5 1975.92
   339.4 1936.69   359.4 1920.26   379.3 1911.98   399.3  1910.9   419.3 1910.82
   428.8 1910.79   487.5    1916   526.6 1922.82   546.2 1930.86   585.3 1953.03
   604.9  1965.2   624.4 1984.99     644 1999.48   692.9 2041.19   712.4 2064.22
   741.8 2084.13   771.1 2100.73   790.6 2114.56   810.2 2132.45     820 2137.68
#Mann= 3 , 0 , 0
       0      .1       0   399.3    .045       0   419.3      .1       0
Bank Sta=399.3,419.3
XS Rating Curve= 0 ,0
Exp/Cntr=0.3,0.1

Type RM Length L Ch R = 1 ,3098    ,421.6,426.9,429.3
XS GIS Cut Line= 3
     1951154.343      171138.945     1951571.688      171156.157
     1951973.834      171225.337
#Sta/Elev= 30
       0 2115.09      10 2112.24    69.6  2079.7    89.5 2061.54   149.2 2023.47
   159.1 2016.19     179 1998.96   238.7 1965.13   258.6 1949.86   288.4 1936.17
   318.2 1924.01   338.1 1913.26     358 1907.55   387.9 1901.12   407.7 1898.42
   427.7 1898.68   447.6 1900.05   457.5 1904.82   467.5 1912.37   487.4 1930.58
   497.3 1946.64   576.9 2010.06   586.9  2025.2   656.6 2078.16   666.5 2091.34
   676.5  2099.3   736.2 2127.11   756.1 2141.23   815.8 2168.64   825.8 2175.27
#Mann= 3 , 0 , 0
       0      .1       0   407.7    .045       0   427.7      .1       0
Bank Sta=407.7,427.7
XS Rating Curve= 0 ,0
Exp/Cntr=0.3,0.1

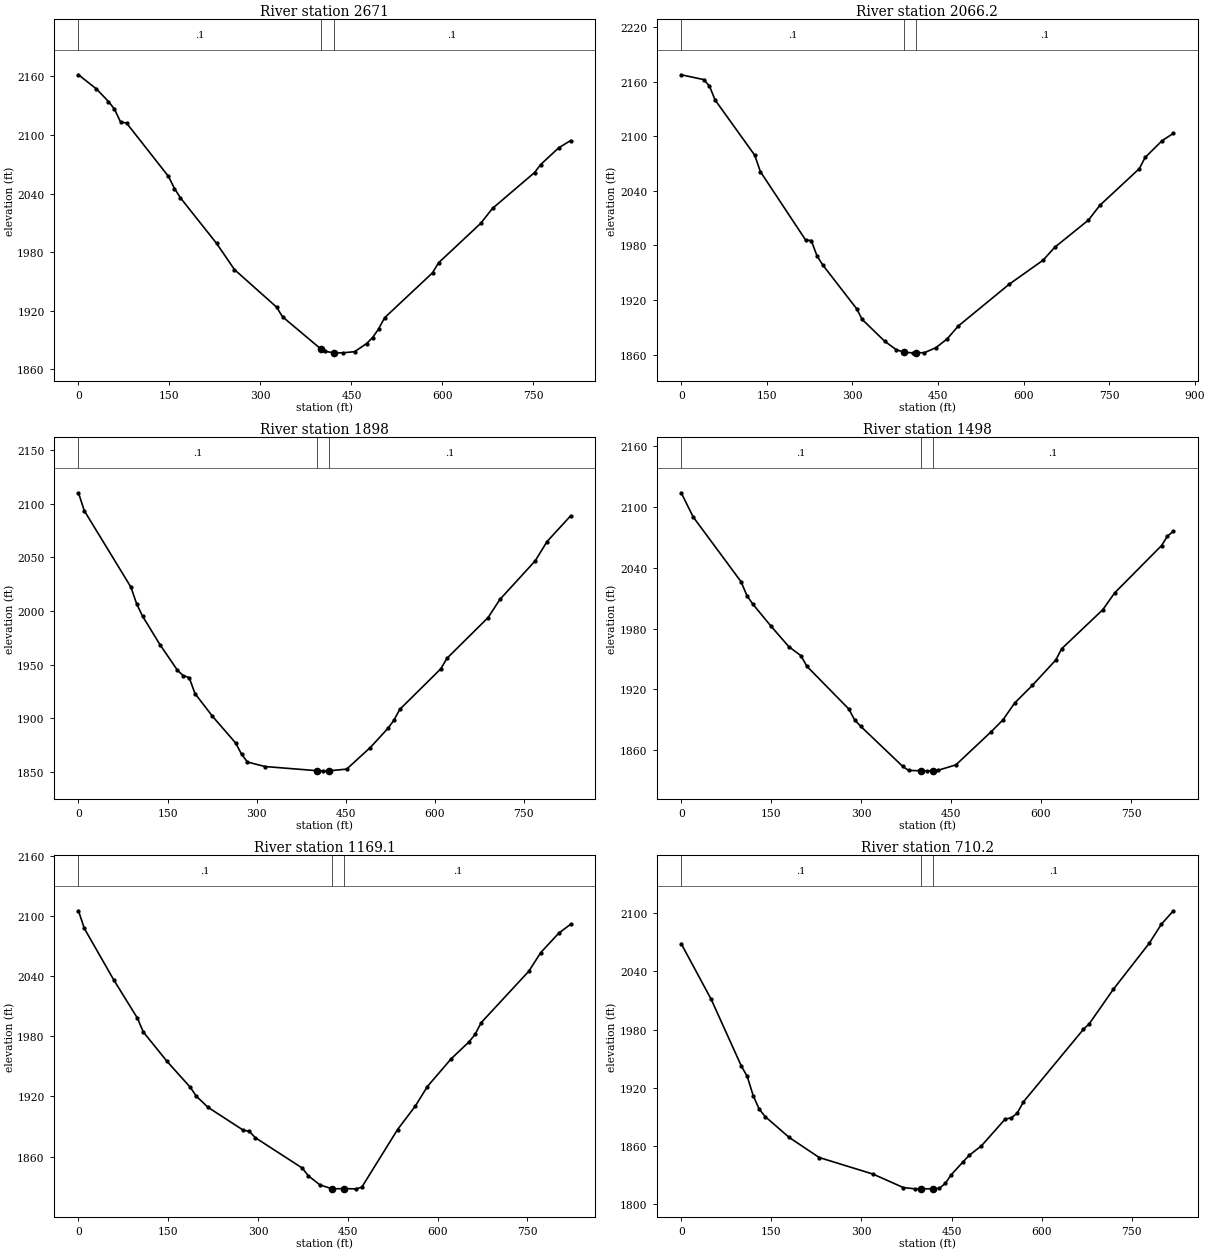
Type RM Length L Ch R = 1 ,2671    ,613.8,604.6,595.2
XS GIS Cut Line= 2
     1951082.854      171471.349      1951868.97      171671.895
#Sta/Elev= 30
       0  2161.7    29.7 2147.15    49.5  2134.3    59.4 2126.44    69.3 2113.42
    79.2 2112.26   148.4 2057.52   158.3  2045.1   168.2 2035.47   227.6 1988.94
   257.2 1962.01   326.5 1923.63   336.4 1913.67   400.5 1880.18   405.6 1878.31
   420.5 1876.82   435.3  1876.7   455.1 1877.88   474.9 1886.15   484.8 1892.31
   494.7 1901.12   504.6 1912.62   583.7 1958.73   593.6 1968.98   662.9  2009.3
   682.7 2024.83   751.9 2061.51   761.8 2069.61   791.5 2086.76   811.3 2094.28
#Mann= 3 , 0 , 0
       0      .1       0   400.5    .045       0   420.5      .1       0
Bank Sta=400.5,420.5
XS Rating Curve= 0 ,0
Exp/Cntr=0.3,0.1

Type RM Length L Ch R = 1 ,2066.2  ,173.1,168.3,165.1
XS GIS Cut Line= 2
     1950931.834      172179.177     1951788.364      172083.248
#Sta/Elev= 30
       0 2167.54    39.6 2162.22    49.5 2155.09    59.4 2139.82   128.8 2079.11
   138.7 2061.07     218 1985.87   227.8 1985.37   237.8 1968.58   247.7  1958.7
   307.1 1910.58     317 1898.66   356.6  1874.6   376.5 1865.51     391 1862.49
   406.2 1861.98     411 1861.99     426 1862.18   445.8 1867.53   465.6 1877.19
   485.4 1891.53   574.6 1937.45     634  1963.9   653.8 1977.75   713.3 2007.92
   733.1 2024.01   802.4 2064.44   812.4 2076.64   842.1 2095.03   861.9 2103.18
#Mann= 3 , 0 , 0
       0      .1       0     391    .045       0     411      .1       0
Bank Sta=391,411
XS Rating Curve= 0 ,0
Exp/Cntr=0.3,0.1

Type RM Length L Ch R = 1 ,1898    ,383.9,399.7,412.4
XS GIS Cut Line= 3
     1950983.029      172417.816     1951375.936      172294.078
     1951780.656      172195.016
#Sta/Elev= 30
       0  2110.1     9.8 2093.41    88.3 2022.25    98.1 2006.47   107.9 1995.22
   137.3 1968.65   166.7 1944.82   176.5 1939.82   186.4 1938.04   196.2 1923.14
   225.6 1902.03   264.8 1877.01   274.6 1866.65   284.4 1859.43   313.8 1855.23
   401.9 1851.32   411.9  1851.2   421.9 1851.23   451.6 1852.81   491.3 1872.89
   521.1  1890.8     531 1898.25   540.9 1908.39   610.3 1946.34   620.3 1955.93
   689.7 1993.93   709.6 2010.82   769.1 2046.79   788.9 2064.69   828.6 2088.63
#Mann= 3 , 0 , 0
       0      .1       0   401.9    .045       0   421.9      .1       0
Bank Sta=401.9,421.9
XS Rating Curve= 0 ,0
Exp/Cntr=0.3,0.1

Type RM Length L Ch R = 1 ,1498    ,323.9,328.7,335.3
XS GIS Cut Line= 3
     1950973.669      172547.081     1951361.593      172677.115
     1951758.572       172785.66
#Sta/Elev= 30
       0 2114.13      20 2090.26    99.8 2026.38   109.8 2012.37   119.8 2003.95
   149.7 1982.51   179.6 1962.15   199.6 1953.36   209.6 1942.86   279.4 1900.76
   289.4  1889.8   299.4  1883.6   369.2 1844.17   379.2 1840.02   399.1 1839.78
   409.1 1839.66   419.1 1839.68   428.7 1840.28   458.1 1845.55   516.9 1878.26
   536.5 1889.94   556.1 1906.62   585.5 1923.96   624.7  1949.1   634.5 1960.18
   703.1 1998.75   722.7 2015.24   801.1 2062.06   810.9 2071.45   820.7 2076.03
#Mann= 3 , 0 , 0
       0      .1       0   399.1    .045       0   419.1      .1       0
Bank Sta=399.1,419.1
XS Rating Curve= 0 ,0
Exp/Cntr=0.3,0.1

Type RM Length L Ch R = 1 ,1169.1  ,453.3,458.9,464.2
XS GIS Cut Line= 3
     1950900.847      172807.734     1951274.649      172984.355
     1951628.183      173189.627
#Sta/Elev= 30
       0 2105.34     9.8 2087.73    59.1 2036.21    98.4 1998.26   108.3 1984.38
   147.6 1955.29     187 1929.03   196.9 1920.24   216.6  1909.1   275.6 1886.22
   285.5 1885.23   295.3 1878.91     374 1848.47   383.9 1840.85   403.6 1831.63
   423.7 1827.84   443.7 1827.98   463.3 1827.78   473.2 1829.28   533.1 1886.97
     563 1910.61   582.9 1929.89   622.8  1957.7   652.7 1974.61   662.7 1982.06
   672.7  1993.6   752.4 2045.02   772.4 2063.67   802.3 2082.94   822.2 2091.85
#Mann= 3 , 0 , 0
       0      .1       0   423.7    .045       0   443.7      .1       0
Bank Sta=423.7,443.7
XS Rating Curve= 0 ,0
Exp/Cntr=0.3,0.1

Type RM Length L Ch R = 1 ,710.2   ,404.7,400,395.2
XS GIS Cut Line= 3
     1950747.468      173108.219     1951050.869      173383.242
     1951354.271      173658.265
#Sta/Elev= 30
       0 2068.47    49.9 2011.17    99.9 1942.67   109.9 1931.71   119.8 1911.99
   129.8 1898.05   139.8 1890.36   179.8 1868.83   229.7  1848.2   319.6 1831.05
   369.6 1817.27   389.5 1815.94   399.5    1816   419.5 1815.97   429.5 1816.44
   439.5 1821.59   449.4 1830.46   469.4 1844.01   479.4 1850.55   499.4 1860.09
   539.3  1887.9   549.3 1889.01   559.3 1893.96   569.3 1905.37   669.2 1980.13
   679.2 1986.07   719.1 2021.44     779    2069     799 2088.44     819 2102.35
#Mann= 3 , 0 , 0
       0      .1       0   399.5    .045       0   419.5      .1       0
Bank Sta=399.5,419.5
XS Rating Curve= 0 ,0
Exp/Cntr=0.3,0.1

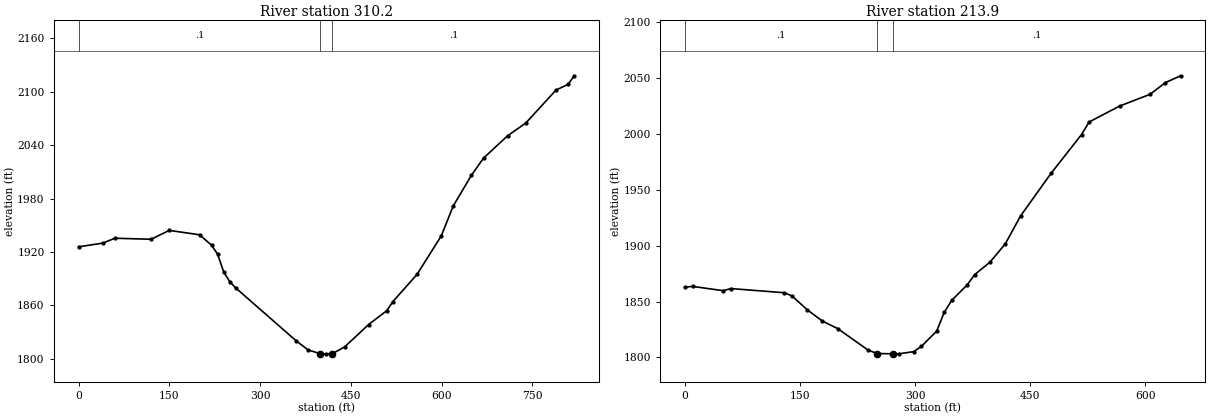
Type RM Length L Ch R = 1 ,310.2   ,96.4,96.2,96
XS GIS Cut Line= 3
     1950472.752      173496.627     1950822.258      173710.022
     1951172.346      173922.456
#Sta/Elev= 30
       0 1925.87      40 1930.07    59.9 1935.52   119.8 1934.37   149.8 1944.31
   199.8 1939.41   219.7 1927.68   229.7 1917.56   239.7 1897.78   249.7 1886.78
   259.7 1879.67   359.6 1820.26   379.5 1810.03   399.5 1805.83   409.5  1805.7
   419.5 1805.95   439.5 1813.41   479.4 1838.64   509.4 1854.25   519.4 1864.39
   559.3 1894.91   599.3 1938.08   619.2 1971.86   649.2 2006.23   669.2 2025.49
   709.1 2050.64   739.1 2064.92     789  2101.9     809 2108.34     819 2117.95
#Mann= 3 , 0 , 0
       0      .1       0   399.5    .045       0   419.5      .1       0
Bank Sta=399.5,419.5
XS Rating Curve= 0 ,0
Exp/Cntr=0.3,0.1

Type RM Length L Ch R = 1 ,213.9   ,199.5,213.9,228.4
XS GIS Cut Line= 2
      1950546.95      173657.219     1951101.122      173989.121
#Sta/Elev= 30
       0 1862.96     9.9  1863.6    49.7 1859.77    59.6 1861.68   129.2 1857.95
   139.1 1855.17     159 1842.82   178.9 1832.59   198.8 1825.88   238.5 1806.59
   250.4 1803.49   270.4 1803.25   278.3 1803.21   298.1 1805.19   308.1 1809.93
     328 1823.56   337.9 1840.52   347.8  1851.3   367.7 1864.91   377.6 1874.23
   397.5 1885.36   417.4  1901.7   437.3  1926.7     477 1964.83   516.8 1999.61
   526.7 2010.88   566.5 2025.15   606.2 2035.68   626.1 2046.14     646 2052.26
#Mann= 3 , 0 , 0
       0      .1       0   250.4    .045       0   270.4      .1       0
Bank Sta=250.4,270.4
XS Rating Curve= 0 ,0
Exp/Cntr=0.3,0.1

Chan Stop Cuts=-1
Use User Specified Reach Order=0
Composite Channel Slope=5